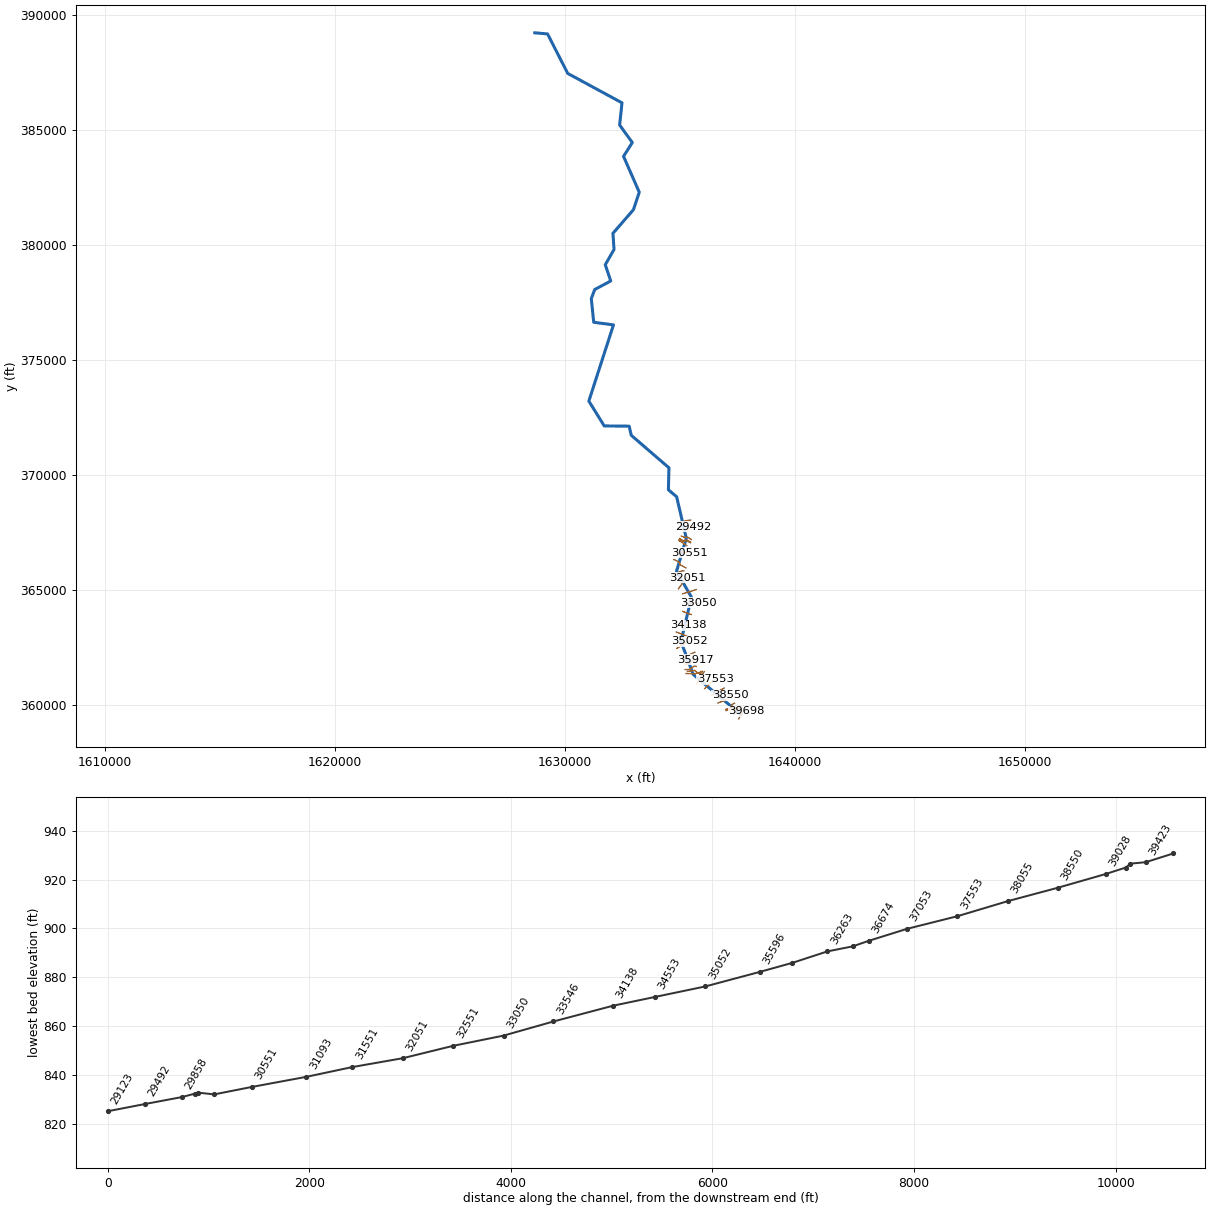
--- PINEYFK.prj (project) ---

Proj Title=PINEYFK
Current Plan=p01
Default Exp/Contr=0,0
English Units
Geom File=g01
Flow File=f01
Plan File=p01
BEGIN DESCRIPTION:
---------- MODELED AS PART OF WVEMD CTP PROGRAM, 2023----------
Stream Name: Piney Fork
Flood Zone:  AFH
Wetzel County, WV
HEC-RAS Version: RAS 6.3
Vertical Datum: NAVD88
Projection: NAD 1983 StatePlane West Virginia S FIPS 4702 (US Feet)
Terrain: 1-meter West Virginia FEMA R3 South Central (collected 2018-2020)
Land Use: 2019 NLCD
Hydrologic Method:
WV SIR2010-5033 regression equations
Additional Model Notes:
Main stem IS FISHINGCK
END DESCRIPTION:
DSS Export Rating Curves= 0
DSS Export Rating Curve Sorted= 0
DSS Export Volume Flow Curves= 0
DXF OffsetX= 0
DXF OffsetY= 0
DXF ScaleX= 0
DXF ScaleY= 0

--- PINEYFK.p01 (plan) ---

Plan Title=Floodplain
Program Version=6.31
Short Identifier=Floodplain
Geom File=g01
Flow File=f01
Subcritical Flow
K Sum by GR= 0
Std Step Tol= 0.01
Critical Tol= 0.01
Num of Std Step Trials= 20
Max Error Tol= 0.3
Flow Tol Ratio= 0.001
Split Flow NTrial= 30
Split Flow Tol= 0.02
Split Flow Ratio= 0.02
Log Output Level= 0
Friction Slope Method= 1
Unsteady Friction Slope Method= 2
Unsteady Bridges Friction Slope Method= 1
Parabolic Critical Depth
Global Vel Dist= 0 , 0 , 0
Global Log Level= 0
CheckData=True
Encroach Param=-1 ,0,0, 0
Mapping Interval=1HOUR
Computation Time Step Use Courant=        0
Computation Time Step Use Time Series=    0
Computation Time Step Count To Double=0
Computation Time Step Max Doubling=0
Computation Time Step Max Halving=0
Computation Time Step Residence Courant=0
Run HTab= 0
Run UNet= 0
Run Sediment= 0
Run PostProcess= 0
Run WQNet= 0
Run RASMapper=-1
UNET Theta= 0
UNET Theta Warmup= 0
UNET ZTol= 0
UNET ZSATol= 0
UNET MxIter= 0
UNET Max Iter WO Improvement= 0
UNET MaxInSteps= 0
UNET DtIC= 0
UNET DtMin= 0
UNET MaxCRTS= 0
UNET WFStab= 0
UNET SFStab= 0
UNET WFX= 1
UNET SFX= 1
UNET Gravity=32.17405
UNET 1D Methodology=Finite Difference
UNET DSS MLevel= 1
UNET Pardiso=0
UNET DZMax Abort= 0
UNET Use Existing IB Tables= 0
UNET Froude Reduction=False
UNET Froude Limit= 0
UNET Froude Power= 0
UNET D1 Cores= 0
UNET WindReference=Eulerian
UNET WindDragFormulation=Hsu (1988)
UNET D2 Coriolis=0
UNET D2 Cores= 0
UNET D2 Theta= 1
UNET D2 Theta Warmup= 1
UNET D2 Z Tol= 0.01
UNET D2 Volume Tol= 0.01
UNET D2 Max Iterations= 20
UNET D2 Equation= 0
UNET D2 RampUpFraction=0.1
UNET D2 TimeSlices= 1
UNET D2 Turbulence Formulation=Non-Conservative (original)
UNET D2 Eddy Viscosity=0.3
UNET D2 Transverse Eddy Viscosity=0.1
UNET D2 Smagorinsky Mixing=0
UNET D2 BCVolumeCheck=0
UNET D2 Cores=0
UNET D2 SolverType=PARDISO (Direct)
UNET D2 Minimum Iterations= 3
UNET D2 Maximum Iterations= 30
UNET D2 Restart Number= 10
UNET D2 Relaxation Coeff=1.3
UNET D2 SOR Precondition Iterations= 10
UNET D2 ILUT Maximum Fill= 8
UNET D2 ILUT Tolerance=1E-08
UNET D2 Convergence Tolerance=0.00001
UNET D1D2 MaxIter= 0
UNET D1D2 ZTol=0.01
UNET D1D2 QTol=0.1
UNET D1D2 MinQTol=1
Write IC File= 0
Write IC File at Fixed DateTime=0
Write IC File at Sim End=0
Echo Input=False
Echo Parameters=False
Echo Output=False
Write Detailed= 0
HDF Write Warmup=0
HDF Write Time Slices=0
HDF Flush=0
HDF Compression= 1
HDF Chunk Size= 1
HDF Spatial Parts= 1
HDF Use Max Rows=0
HDF Fixed Rows= 1
Calibration Method= 0
Calibration Iterations= 20
Calibration Max Change=0.05
Calibration Tolerance=0.2
Calibration Maximum=1.5
Calibration Minimum=0.5
Calibration Optimization Method= 1
WQ AD Non Conservative
WQ ULTIMATE=-1
WQ Max Comp Step=1HOUR
WQ Output Interval=15MIN
WQ Output Selected Increments= 0
WQ Create Restart=0
WQ Fixed Restart=0
WQ System Summary=0
WQ Write To DSS=0
Sorting and Armoring Iterations= 10
XS Update Threshold= 0.02
Bed Roughness Predictor= 0
Hydraulics Update Threshold= 0.02
Energy Slope Method= 1
Volume Change Method= 1
Sediment Retention Method= 0
Sediment TS Multiplier= 1
Warm Up Method= 0
XS Weighting Method= 0
Number of US Weighted Cross Sections= 1
Number of DS Weighted Cross Sections= 1
Upstream XS Weight=0
Main XS Weight=1
Downstream XS Weight=0
Number of DS XS's Weighted with US Boundary= 1
Upstream Boundary Weight= 1
Weight of XSs Associated with US Boundary= 0
Number of US XS's Weighted with DS Boundary= 1
Downstream Boundary Weight= 0.5
Weight of XSs Associated with DS Boundary= 0.5
Percentile Method= 0
Sediment Output Level= 3
Mass or Volume Output= 0
Output Increment Type= 1
Profile and TS Output Increment= 1
Transport Output Increment 1
XS Output Flag= 0
XS Output Increment= 10
Read HDF5 Sediment Hotstart= 0
Sediment Hotstart Type= 0
Write Gradation File= 0
Read Gradation Hotstart= 0
Write HDF5 File= 1
Write Binary Output= 1
Write DSS Sediment File= 0
DSS Sediment Output Type= 1
SV Curve= 0
Specific Gage Flag= 0
Subcell Erosion Methods= 0
Subcell Deposition Methods= 0
Advection Scheme= 1
Matrix Solver= 0
Implicit Weighting Factor= 1
Maximum Outer Loop Convergence Iterations= 5
Convergence Maximum Absolute= 0.001
Convergence RMSE= 0.0001
Grain Fractions Max Abs Error= 0.001
Max Subgrid Regions= 1
Max Subgrid Length Scale= 3.402823E+38
Initial Layer Thickness= 3.402823E+38
Min Layer Thickness= 3.402823E+38
Max Layer Thickness= 3.402823E+38
Number of Layers= 5

--- PINEYFK.f01 (steady flow) ---

Flow Title=Flow
Program Version=6.31
Number of Profiles= 1
Profile Names=F01pct
River Rch & RM=PINEYFK,Main,39698
     803
River Rch & RM=PINEYFK,Main,36674
    1100
River Rch & RM=PINEYFK,Main,33050
    1230
River Rch & RM=PINEYFK,Main,30180
    1550
River Rch & RM=PINEYFK,Main,26751
    1760
River Rch & RM=PINEYFK,Main,23087
    2690
River Rch & RM=PINEYFK,Main,21442
    3100
River Rch & RM=PINEYFK,Main,13494
    3450
Boundary for River Rch & Prof#=PINEYFK,Main            , 1
Up Type= 0
Dn Type= 3
Dn Slope=0.00335
DSS Import GetInterval= 0
DSS Import GetPeak= 0
DSS Import FillOption= 0

--- PINEYFK.g01 (geometry) ---

Geom Title=Geometry
Program Version=6.31

River Reach=PINEYFK         ,Main
Reach XY= 30
1637652.04090622359572.7565328951635573.92599796361325.189005534
1635044.14299794362755.4540055531635498.69102436 364679.07949232
1634850.03899795365811.5880055541635275.39778208367236.421113468
1634854.89098061369042.9405269331634496.50099794369345.630005537
1634519.76599794370302.4640055011632880.90199792371715.616005527
1632791.97299794372111.9070055331631706.87599796372122.147005523
 1631039.3829979373202.5090055321632109.42999795  376512.4290055
1631251.80099796376627.5140055441631145.89799796  377655.3210055
1631294.65199793378050.1610055391631990.05999793378422.963005515
1631753.15599793379128.7770055261632134.52799795  379792.3530055
1632086.16799794380491.4340055181632976.23999795 381518.30879982
1633230.28499795382277.7010055441632547.11999794383836.859005501
1632927.26799793384439.2190055461632376.32899796385198.902005529
1632479.78299795386163.6580055441630120.85799794387442.351005578
1629244.05699794389158.7350055211628689.62299958 389206.28400109

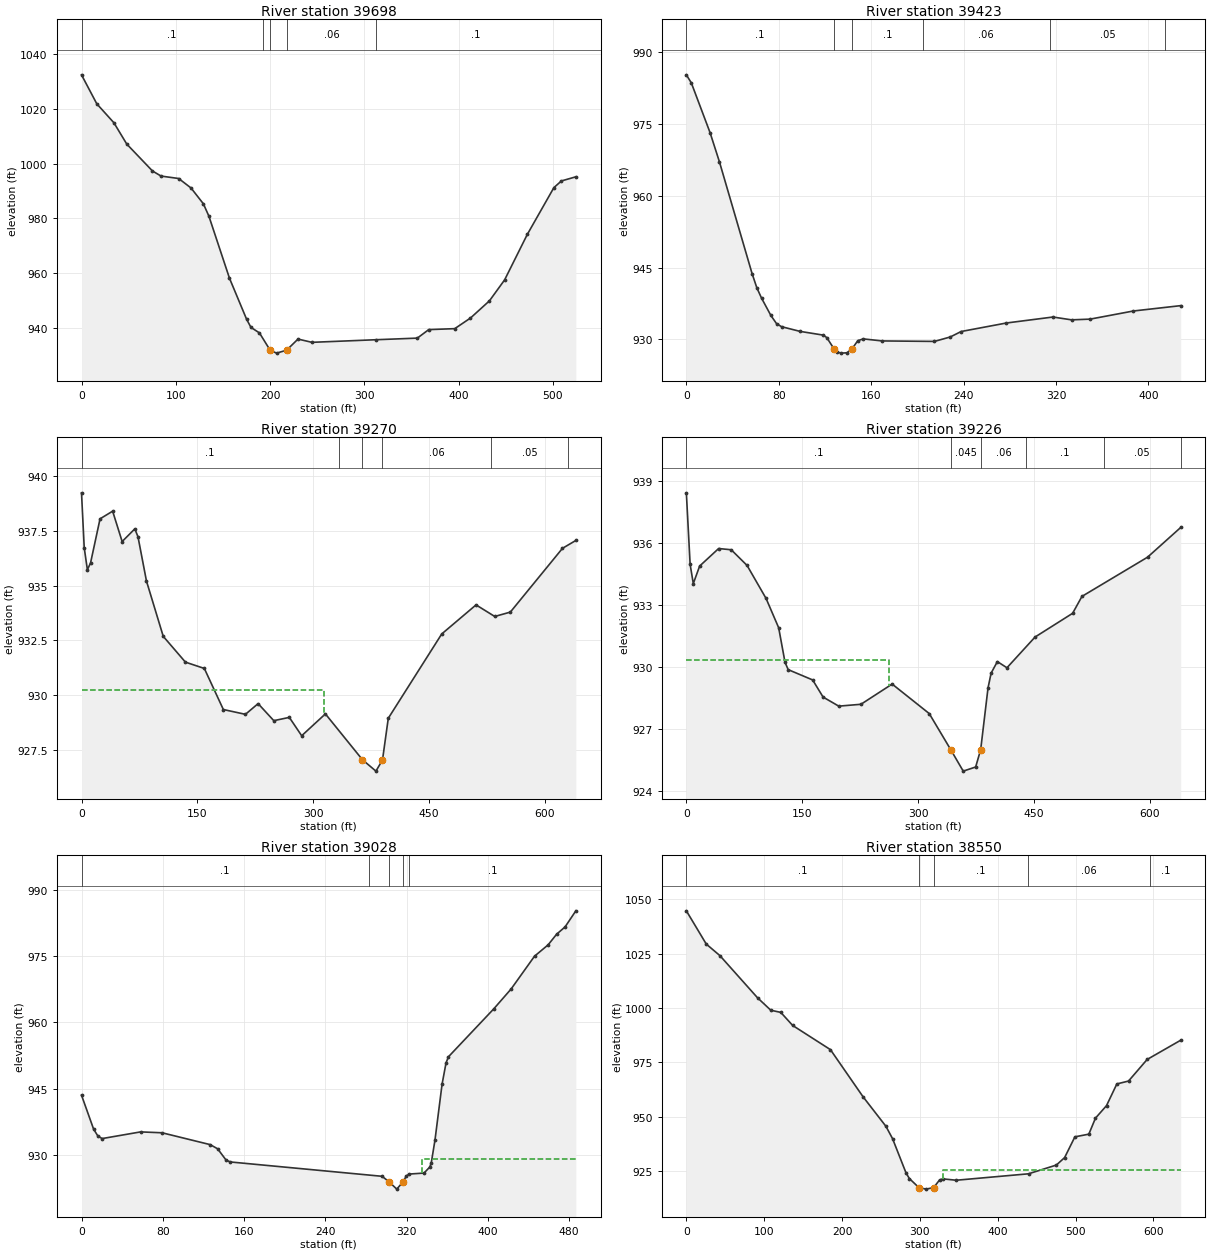
Type RM Length L Ch R = 1 ,39698   ,274.8,274.6,273.7
XS GIS Cut Line= 6
1637551.25277242359390.2685102621637592.73694143359467.309694762
1637628.29461309359533.3446676831637675.70462327359621.391735683
1637719.34837936359703.5992055411637887.32201193  359721.7274892
#Sta/Elev= 30
       0  1032.5    16.2 1021.91    34.4 1014.95      48 1007.18    75.3  997.33
    84.4  995.47   103.1  994.58   116.2  991.11   129.3  985.33   135.2  980.77
     157   958.1   175.2  943.07   179.8  940.12   188.8   938.1   200.2  931.74
     207  930.71   217.6931.7841   229.7  935.85   244.5  934.66   312.5  935.61
   356.3   936.2   368.4  939.31     396  939.66   412.7  943.55   432.8  949.83
   448.9  957.49     473  974.14   501.2  991.25   509.2  993.69   524.5   995.2
#Mann= 5 ,-1,0
       0      .1       0   192.5     .06       0   200.2    .045       0
   217.6     .06       0   312.5      .1       0
Bank Sta=200.2,217.6
XS Rating Curve= 0 ,0
Exp/Cntr(USF)=0,0
Exp/Cntr=0.3,0.1

Type RM Length L Ch R = 1 ,39423   ,156.5,152.6,140.6
XS GIS Cut Line= 4
1637365.97279426359580.3192282371637377.86737265 359653.91693201
1637467.82012171359798.1386949611637649.95585327359820.441029437
#Sta/Elev= 30
       0  985.32     4.3  983.64    20.5  973.25    28.6  967.16    56.9  943.76
      61   940.8    65.1  938.62    73.2  934.99    78.1  933.28    82.4  932.65
    98.4  931.67   118.7  930.88   121.6  930.36   127.7928.0668   130.3  927.35
   134.2  927.12   139.1  927.19   143.6  928.07   148.4  929.71   153.1   930.1
   169.5  929.67   214.8  929.57   228.5   930.5   237.9  931.64   277.1  933.42
   317.4  934.67   333.5  934.08   349.6  934.23     387  935.93     428  937.05
#Mann= 6 ,-1,0
       0      .1       0   127.7    .045       0   143.6      .1       0
  204.55     .06       0  314.53     .05       0  414.53      .1       0
Bank Sta=127.7,143.6
XS Rating Curve= 0 ,0
Exp/Cntr(USF)=0,0
Exp/Cntr=0.3,0.1

Type RM Length L Ch R = 1 ,39270   ,49.8,44.5,44.8
XS GIS Cut Line= 6
1637008.69756231359751.9403343951637245.05217859359803.255238381
1637280.67562278359805.786647594 1637401.8516401359808.760292191
1637422.66715228359813.9641702361637639.98597751359845.823877825
#Sta/Elev= 30
       0  939.25     3.5  936.74     7.6  935.73    11.7  936.04      24  938.06
    40.3  938.41    52.6  937.02      69   937.6    73.1  937.24    84.1  935.21
   105.8  932.68   134.5   931.5     159  931.21   183.6  929.33   212.2  929.11
   228.6   929.6   248.9  928.82     269  928.97     285  928.13   315.7  929.13
   363.7  927.03   381.1  926.51   389.6927.0204   397.1  928.93   466.3  932.79
   510.7  934.12   534.9  933.59   555.1  933.79   622.6  936.71   639.9  937.07
#Mann= 6 ,-1,0
       0      .1       0  333.19     .06       0   363.7    .045       0
   389.6     .06       0  530.27     .05       0  630.27      .1       0
#XS Ineff= 2 , 0
          313.36  930.23
Permanent Ineff=
       F       F
Bank Sta=363.7,389.6
XS Rating Curve= 0 ,0
Exp/Cntr(USF)=0,0
Exp/Cntr=0.3,0.1

Type RM Length L Ch R = 1 ,39226   ,168.1,197.8,200.4
XS GIS Cut Line= 6
1637003.29857359359794.8443399091637239.65318987359846.159243895
1637275.27663406359848.6906531081637396.45265138359851.664297705
1637417.26816356 359856.868175751637634.58698879359888.727883339
#Sta/Elev= 30
       0  938.43     4.9  934.96       9  934.03    17.2  934.88    41.8  935.73
    58.1  935.67    78.6  934.91   103.2  933.31   119.5  931.89   127.7  930.22
   131.8  929.86   163.5  929.36     177  928.53   197.3  928.09     226  928.18
   266.4  929.16   314.4  927.73   342.4  925.97   358.4  924.94   374.5  925.14
     381925.9847   390.5  928.97   394.5  929.69   402.6  930.25     415  929.95
   451.4  931.44     500  932.59   512.1  933.41     597  935.31   639.9  936.75
#Mann= 6 ,-1,0
       0      .1       0   342.4    .045       0     381     .06       0
  440.27      .1       0  540.27     .05       0  639.91      .1       0
#XS Ineff= 2 , 0
          262.31  930.32
Permanent Ineff=
       F       F
Bank Sta=342.4,381
XS Rating Curve= 0 ,0
Exp/Cntr(USF)=0,0
Exp/Cntr=0.3,0.1

Type RM Length L Ch R = 1 ,39028   ,480.5,478.1,468.6
XS GIS Cut Line= 4
1636992.78039735359804.0859841541637147.40991639359854.637942302
1637258.92158878360017.4449839831637372.66349461360073.200820175
#Sta/Elev= 30
       0  943.55    11.9  935.88    16.1  934.32    20.3  933.74    58.2  935.25
    79.3  935.05   126.7  932.37     134  931.43   142.4  928.86   146.6  928.45
   295.9  925.21   302.7  923.99   310.4  922.31   316.7924.0007   319.9  925.32
   322.8  925.72   337.2  925.94     343  927.34   344.4  928.32     348  933.39
     355  946.05   358.9  950.86   361.3  952.24   405.9  963.07     423  967.57
     446  974.97   459.4  977.54   467.8  979.95   476.1   981.6   486.7  985.23
#Mann= 5 ,-1,0
       0      .1       0  282.68     .06       0   302.7    .045       0
   316.7     .06       0  322.68      .1       0
#XS Ineff= 2 , 0
                           334.8          929.05
Permanent Ineff=
       F       F
Bank Sta=302.7,316.7
XS Rating Curve= 0 ,0
Exp/Cntr(USF)=0,0
Exp/Cntr=0.3,0.1

Type RM Length L Ch R = 1 ,38550   ,493.5,495.5,495.4
XS GIS Cut Line= 6
1636648.77479875   360076.9625591636736.03741951360116.268582761
1636890.33894818360168.7461680921636983.49525793 360205.81302309
1637041.15032634360264.1390219181637170.35446426360408.820163012
#Sta/Elev= 30
       0  1044.7    25.6  1029.4    43.1 1024.09    91.4  1004.7   108.5  998.96
   121.3  997.97   136.6  991.95   185.1  980.82     227  959.13   256.4  945.54
   264.9  939.85   282.2  924.09   286.5  921.51   298.8917.3328     308  916.65
   317.7917.3812   325.2  920.84   329.5  921.37   346.7  920.74   439.5   923.7
   475.3  927.73   485.9  931.16   499.1  940.71     517  941.94   525.5   949.3
   539.7  955.06     553  965.05     568  966.38   591.9  976.31     635  985.16
#Mann= 5 ,-1,0
       0      .1       0   298.8    .045       0   317.7      .1       0
  438.98     .06       0  595.62      .1       0
#XS Ineff= 2 , 0
                          329.74          925.57
Permanent Ineff=
       F       F
Bank Sta=298.8,317.7
XS Rating Curve= 0 ,0
Exp/Cntr(USF)=0,0
Exp/Cntr=0.3,0.1

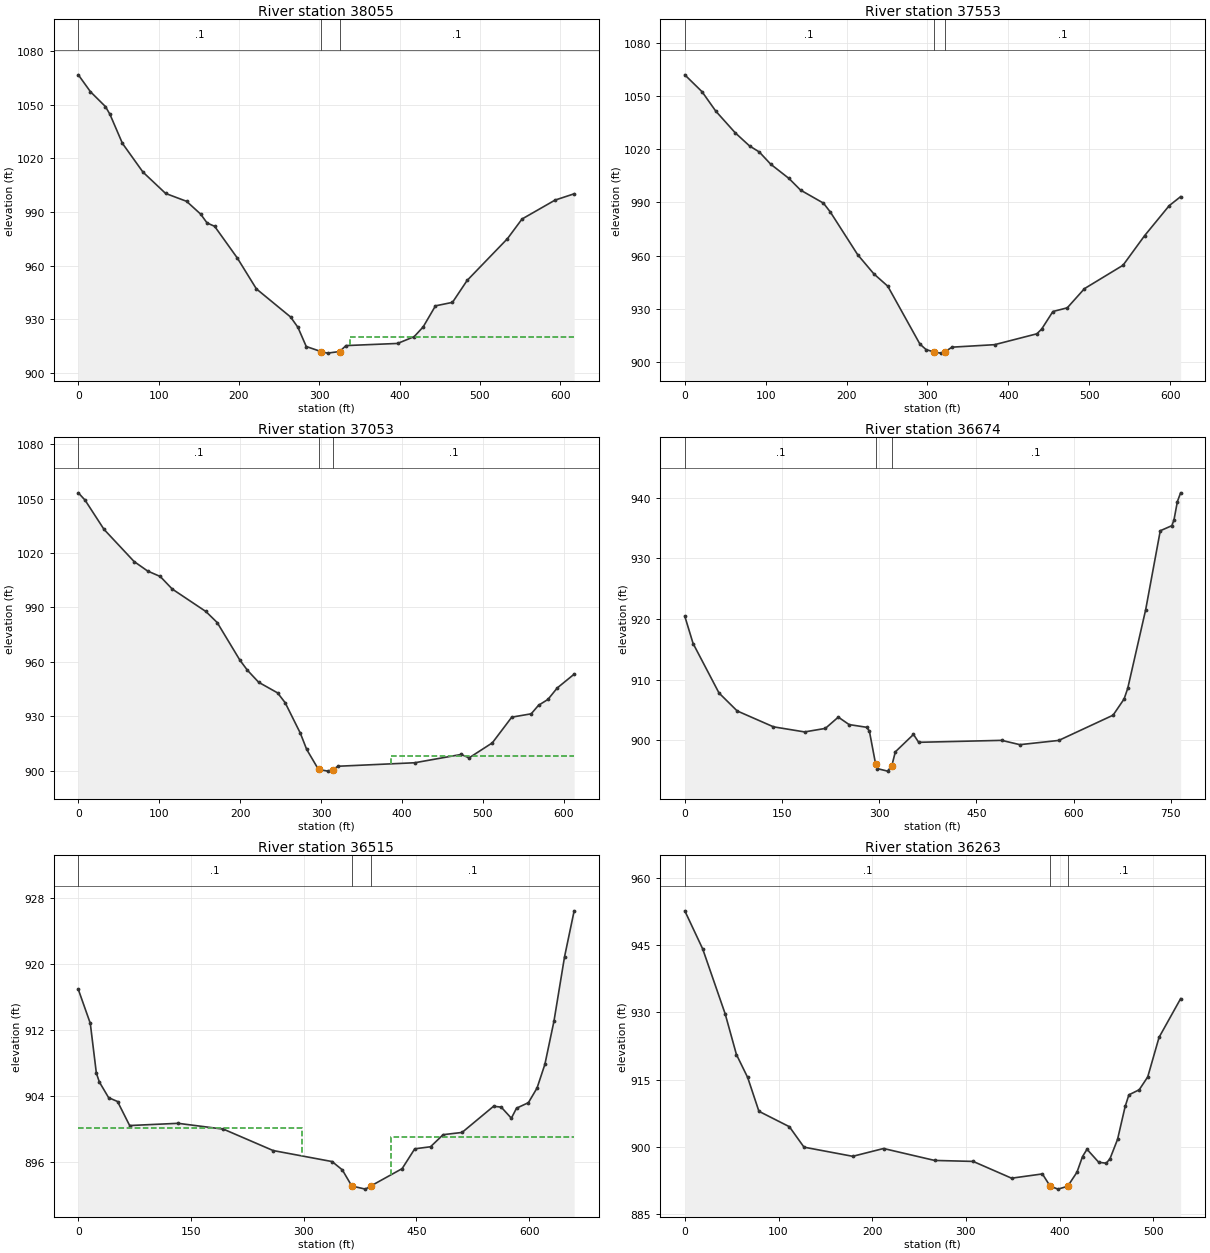
Type RM Length L Ch R = 1 ,38055   ,497.8,501.1,501.9
XS GIS Cut Line= 6
1636387.17722484360420.2226992551636469.30107634360469.710789248
1636545.43182959360516.8091202531636609.47041543360557.296900168
 1636696.2819216360606.9683887511636921.03803375360730.048523173
#Sta/Elev= 30
       0 1066.64    15.1  1057.2    33.8 1048.89    39.4 1044.54    54.9 1028.36
    80.5 1012.29   108.7 1000.38   134.8  995.98   152.3  988.84   160.3  983.89
   169.7  982.03     198  964.29   221.7  947.07   264.2  931.41   273.4  925.62
   283.8  914.88   302.6     912   310.3  911.18   325.4912.0749   333.3  915.39
   397.5  916.59   418.2  920.38   429.4  925.84   444.7  937.59   465.9  939.54
   484.1  951.77   534.3   975.1   552.5   986.1   593.6  996.66   617.4 1000.18
#Mann= 3 ,-1,0
       0      .1       0   302.6    .045       0   325.4      .1       0
#XS Ineff= 2 , 0
                          337.91          919.91
Permanent Ineff=
       F       F
Bank Sta=302.6,325.4
XS Rating Curve= 0 ,0
Exp/Cntr(USF)=0,0
Exp/Cntr=0.3,0.1

Type RM Length L Ch R = 1 ,37553   ,498.1,500,502.4
XS GIS Cut Line= 6
1636073.60272075360704.9540851711636137.73284183360773.917201832
1636203.91545226360831.1546201711636393.00759375360994.690710425
1636459.19053225 361051.927800671636529.54636267361113.894212171
#Sta/Elev= 30
       0 1061.86    21.3 1052.35    38.3  1041.4    62.4 1029.15      80 1021.79
    92.1 1018.37   106.2 1011.49   128.8 1003.44   143.1  996.89   171.4  989.54
     180  984.47   213.7  960.48   233.8  949.63   250.9  942.73   290.6  910.13
   298.3  906.98   307.6  905.72   316.1     905   321.6905.7587   330.3  908.36
   382.9  909.76   435.2  915.89   441.1  918.54     455  928.45   472.8  930.54
     494  941.34   541.7  954.53   568.4  971.22   598.8  988.13   612.9   993.2
#Mann= 3 ,-1,0
       0      .1       0   307.6    .045       0   321.6      .1       0
Bank Sta=307.6,321.6
XS Rating Curve= 0 ,0
Exp/Cntr(USF)=0,0
Exp/Cntr=0.3,0.1

Type RM Length L Ch R = 1 ,37053   ,392.1,379.6,366
XS GIS Cut Line= 6
1635727.65721843360921.6295048451635776.30049384361001.773701504
1635859.90728201361141.1156144291635911.71787393361226.648251757
1635952.61739843361289.5729946791636052.93347076361440.755435094
#Sta/Elev= 30
       0 1053.13     8.3 1049.11    31.7 1033.02    68.9 1015.29    85.7 1010.04
   101.2 1007.05     116 1000.15   157.6  987.76   171.6  981.68   199.6  960.99
   208.9  955.43   222.9  948.76   246.2  942.94   255.6  937.51   274.3  920.76
   282.2  911.77   296.8  900.73   308.4  899.83   314.1900.6954     321  902.52
   415.7  904.44   473.2  909.02   482.8  907.12   511.6  915.41   535.6  929.56
   559.6   931.4   568.7  936.11   580.3  939.32   591.8  945.65   612.7  953.24
#Mann= 3 ,-1,0
       0      .1       0   296.8    .045       0   314.1      .1       0
#XS Ineff= 2 , 0
                          386.35          908.04
Permanent Ineff=
       F       F
Bank Sta=296.8,314.1
XS Rating Curve= 0 ,0
Exp/Cntr(USF)=0,0
Exp/Cntr=0.3,0.1

Type RM Length L Ch R = 1 ,36674   ,170.1,158.8,148.4
XS GIS Cut Line= 3
1635263.32268728361360.2913944231635886.65040727361349.464362066
1635979.45354176361456.187966729
#Sta/Elev= 30
       0  920.45    12.8  915.96    52.8   907.8    80.8  904.85   136.8  902.23
   184.8  901.39   216.8  901.97   236.8  903.83   253.5   902.6   280.8  902.15
   284.8   901.5   294.5896.0254   296.8  895.35   312.8  894.93   319.4895.8345
   324.8  898.11   352.8  900.98   360.8  899.68   488.9     900   516.9  899.29
   576.9  899.99   660.7  904.15   677.7  906.82   683.3  908.57     711  921.54
   733.5  934.54   751.4  935.38   754.7  936.36   759.9  939.35   764.9  940.79
#Mann= 3 ,-1,0
       0      .1       0   294.5    .045       0   319.4      .1       0
Bank Sta=294.5,319.4
XS Rating Curve= 0 ,0
Exp/Cntr(USF)=0,0
Exp/Cntr=0.3,0.1

Type RM Length L Ch R = 1 ,36515   ,228.5,251.6,269.1
XS GIS Cut Line= 6
1635320.28658491361451.5167515821635629.43504807361496.474980587
1635670.32266128361479.3765241551635708.32211473361427.429004861
 1635838.2628826361386.064909712 1635913.0086831361453.688092388
#Sta/Elev= 30
       0  916.93    15.9  912.82      24  906.76      28  905.68    40.3  903.78
    52.2  903.31    68.3  900.39   132.8  900.66   193.2  899.95   259.3  897.35
   337.8  896.01   351.4     895     364  893.04   382.1  892.66   389.8893.0663
     431  895.15   447.8  897.56   468.8  897.81   485.6  899.28   510.8  899.55
   552.7  902.73   562.9  902.63   576.4  901.28   583.3   902.5   599.1  903.17
   610.6  904.95     621  907.82   633.1  913.07   647.2   920.9     660  926.49
#Mann= 3 ,-1,0
       0      .1       0     364    .045       0   389.8      .1       0
#XS Ineff= 2 , 0
          298.26  900.14  416.37          899.05
Permanent Ineff=
       F       F
Bank Sta=364,389.8
XS Rating Curve= 0 ,0
Exp/Cntr(USF)=0,0
Exp/Cntr=0.3,0.1

Type RM Length L Ch R = 1 ,36263   ,344.9,346.6,329
XS GIS Cut Line= 4
1635225.01938289 361532.158715751635433.17450467361539.592827242
1635605.64589129361680.8409455961635703.03275184361671.176600656
#Sta/Elev= 30
       0  952.67    19.1  944.17    43.1  929.68    55.1  920.62    67.1   915.5
    79.1  907.96   111.6  904.52   127.2  899.96   179.2  897.92   212.1  899.66
   266.6     897   307.7  896.78   348.7  893.04   381.6  893.99   389.8891.2792
   398.2   890.6   408.6  891.24   418.5  894.38   424.4  897.86   429.2  899.49
   441.7  896.59   449.8  896.38   453.8  897.42   461.8   901.7   469.9  909.03
   473.9  911.63   484.9  912.76     494  915.63   506.1  924.46   529.1  933.08
#Mann= 3 ,-1,0
       0      .1       0   389.8    .045       0   408.6      .1       0
Bank Sta=389.8,408.6
XS Rating Curve= 0 ,0
Exp/Cntr(USF)=0,0
Exp/Cntr=0.3,0.1

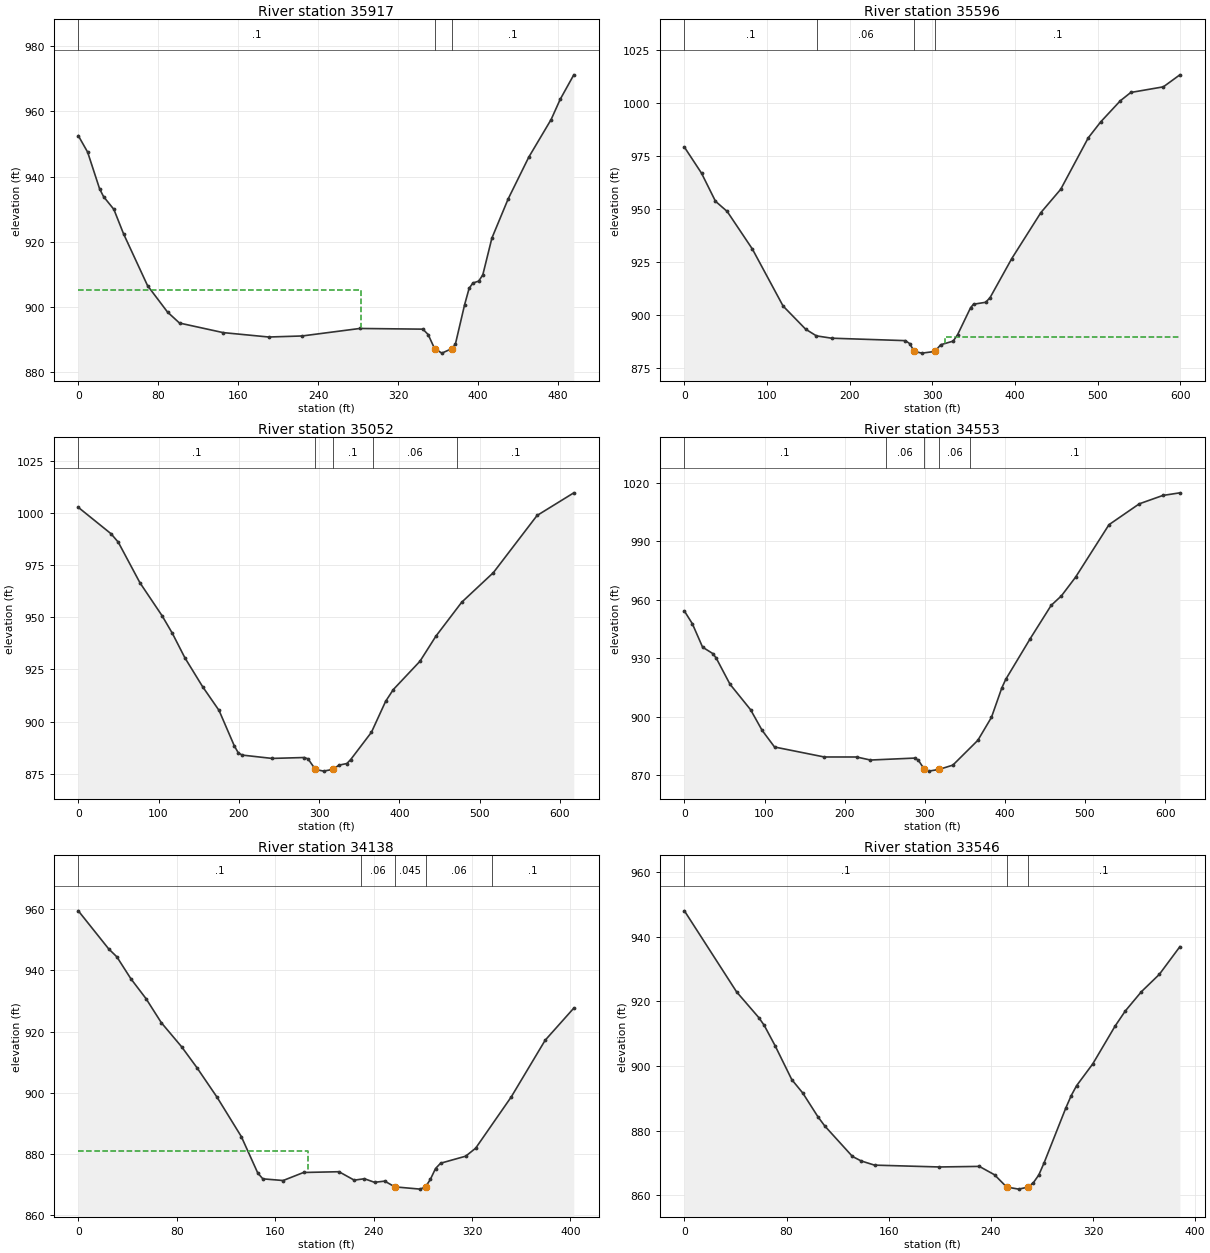
Type RM Length L Ch R = 1 ,35917   ,318.5,321.1,321.8
XS GIS Cut Line= 3
1635206.81631129361774.0467060751635321.59504424 361774.79803434
1635656.08600346361957.777869577
#Sta/Elev= 30
       0  952.58     9.3  947.56    21.3   936.3    25.3  933.89    35.6  929.99
    45.3  922.49    69.3  906.62    89.3  898.51   101.3  895.14     145  892.21
   190.6  890.86     224  891.18   281.8  893.48   344.9  893.27   350.2  891.62
   356.6  887.33   363.9  885.92   374.2887.3298   377.5  888.72   386.7  900.77
   391.2  905.77     395  907.42   400.8  907.99   404.9  909.91     414  921.18
   430.3   933.2   450.9  945.99   473.3  957.54   482.4  963.74     496  971.24
#Mann= 3 ,-1,0
       0      .1       0   356.6    .045       0   374.2      .1       0
#XS Ineff= 2 , 0
           282.9  905.16
Permanent Ineff=
       F       F
Bank Sta=356.6,374.2
XS Rating Curve= 0 ,0
Exp/Cntr(USF)=0,0
Exp/Cntr=0.3,0.1

Type RM Length L Ch R = 1 ,35596   ,543.1,543.2,539.7
XS GIS Cut Line= 3
1635148.37511453361955.209824053 1635419.9027867 362186.14374539
1635641.84025789362285.317454799
#Sta/Elev= 30
       0   979.4    20.7  967.11    37.6  953.86    51.8  949.04    82.3  931.29
   119.4  904.45   146.7  893.53   159.7  890.38   178.2  889.28   267.5  888.13
   272.7  886.68     278  883.03   287.4  882.24     303883.0248   310.1  886.19
   325.2  887.91   330.5  890.91   346.2  903.62   349.8   905.3   364.5  906.22
   369.8   908.4   396.1  926.85   431.3  948.52   455.3  959.51   488.6  983.76
   503.8  991.35   527.5 1001.28   540.1 1005.17   579.5 1007.83   599.5 1013.49
#Mann= 4 ,-1,0
       0      .1       0     160     .06       0     278    .045       0
     303      .1       0
#XS Ineff= 2 , 0
                          314.72          889.66
Permanent Ineff=
       F       F
Bank Sta=278,303
XS Rating Curve= 0 ,0
Exp/Cntr(USF)=0,0
Exp/Cntr=0.3,0.1

Type RM Length L Ch R = 1 ,35052   ,507.8,499.5,487.6
XS GIS Cut Line= 6
1634863.94601934362458.0050410031634947.62859476 362501.52759175
1635021.61663575362548.320805252 1635228.5958806362688.533451334
1635301.89265001 362736.347332091635394.76680809362767.891888425
#Sta/Elev= 30
       0 1002.64    40.8  989.99    49.8  985.95    76.8  966.51   104.4  950.71
   117.2  942.29   132.8  930.57   154.8  916.79   175.4  905.33   194.5  888.29
   199.4  885.01   204.2  883.95   241.4  882.35   281.5  882.78   286.3  882.13
   295.5877.0656   305.7  876.26   316.8 877.074     325  879.13   334.7  879.91
   339.4  881.78   365.3  894.88     383  909.71   392.6  915.36   425.8  928.91
   445.6   940.9   477.8  957.18   517.3  971.38   571.7  998.74   617.5  1009.6
#Mann= 5 ,-1,0
       0      .1       0   295.5    .045       0   316.8      .1       0
  366.87     .06       0  471.87      .1       0
Bank Sta=295.5,316.8
XS Rating Curve= 0 ,0
Exp/Cntr(USF)=0,0
Exp/Cntr=0.3,0.1

Type RM Length L Ch R = 1 ,34553   ,414.1,414.9,415.8
XS GIS Cut Line= 6
1634838.84108268363164.3225260081635078.58830659363073.849609837
1635171.79382885363037.6046035891635239.95084475 363004.39338392
1635324.56123984362973.6283535961635416.34583317362944.198950499
#Sta/Elev= 30
       0  954.23     9.9  947.71    22.7  935.66    35.6  932.33    39.8  929.98
    56.9  916.63    82.6  903.53      97  892.92   112.5  884.36   174.6  879.23
     215  879.22   232.2  877.66   287.9  878.67   292.2  877.48   299.6872.8412
   305.1  871.96     318  872.85   335.1  875.05   366.3   887.8   383.3  899.61
   396.2  914.72   401.1  919.11   431.7  940.06   457.8  957.14   470.6  962.02
   488.3  971.64     530   998.6   567.8 1009.32   597.2 1013.62   618.5 1014.97
#Mann= 5 ,-1,0
       0      .1       0  251.25     .06       0   299.6    .045       0
     318     .06       0  356.25      .1       0
Bank Sta=299.6,318
XS Rating Curve= 0 ,0
Exp/Cntr(USF)=0,0
Exp/Cntr=0.3,0.1

Type RM Length L Ch R = 1 ,34138   ,591,592.4,589.5
XS GIS Cut Line= 3
1634950.70730581363521.1885603591635247.66931279363445.683009892
1635343.17922043363458.906894042
#Sta/Elev= 30
       0  959.52    24.7  947.05    31.3  944.47    42.7  937.29    55.1  930.73
    67.5  922.88      84  914.99    96.4  908.18   112.9  898.41   132.5   885.6
   145.9  873.65     150  871.75   166.5   871.2   183.1  873.83   211.9  874.08
   224.3  871.32   232.6  871.78   240.8  870.61   249.1     871   257.3  869.12
     278  868.38   282.3869.1456   286.2  871.58   290.4  875.13   294.5  876.86
   314.9  879.17     323  881.78   351.9  898.55   379.5  917.13   402.8  927.66
#Mann= 5 ,-1,0
       0      .1       0     230     .06       0   257.3    .045       0
   282.3     .06       0  336.41      .1       0
#XS Ineff= 2 , 0
          186.35  880.71
Permanent Ineff=
       F       F
Bank Sta=257.3,282.3
XS Rating Curve= 0 ,0
Exp/Cntr(USF)=0,0
Exp/Cntr=0.3,0.1

Type RM Length L Ch R = 1 ,33546   ,492,495.3,499.1
XS GIS Cut Line= 3
1635122.28141129364063.1722118621635337.39794854363975.207499551
1635484.61520272363924.500039269
#Sta/Elev= 30
       0  947.96    40.9  922.89    58.2  914.98    62.5  912.57    71.1  906.21
    84.1  895.78    92.7  891.64   104.6  884.28     110  881.42   131.6  872.03
   138.4  870.64   148.9  869.34   199.7  868.77     231  868.95   242.9  866.36
   252.4  862.57   261.8  861.92   269.1  862.54   273.4  863.94   277.6  866.31
   281.8  870.11   298.7  886.96     303  890.86   307.2  893.91   319.9  900.67
   337.3   912.3   345.3  916.98     358  922.98     372  928.32   388.1  936.88
#Mann= 3 ,-1,0
       0      .1       0   252.4    .045       0   269.1      .1       0
Bank Sta=252.4,269.1
XS Rating Curve= 0 ,0
Exp/Cntr(USF)=0,0
Exp/Cntr=0.3,0.1

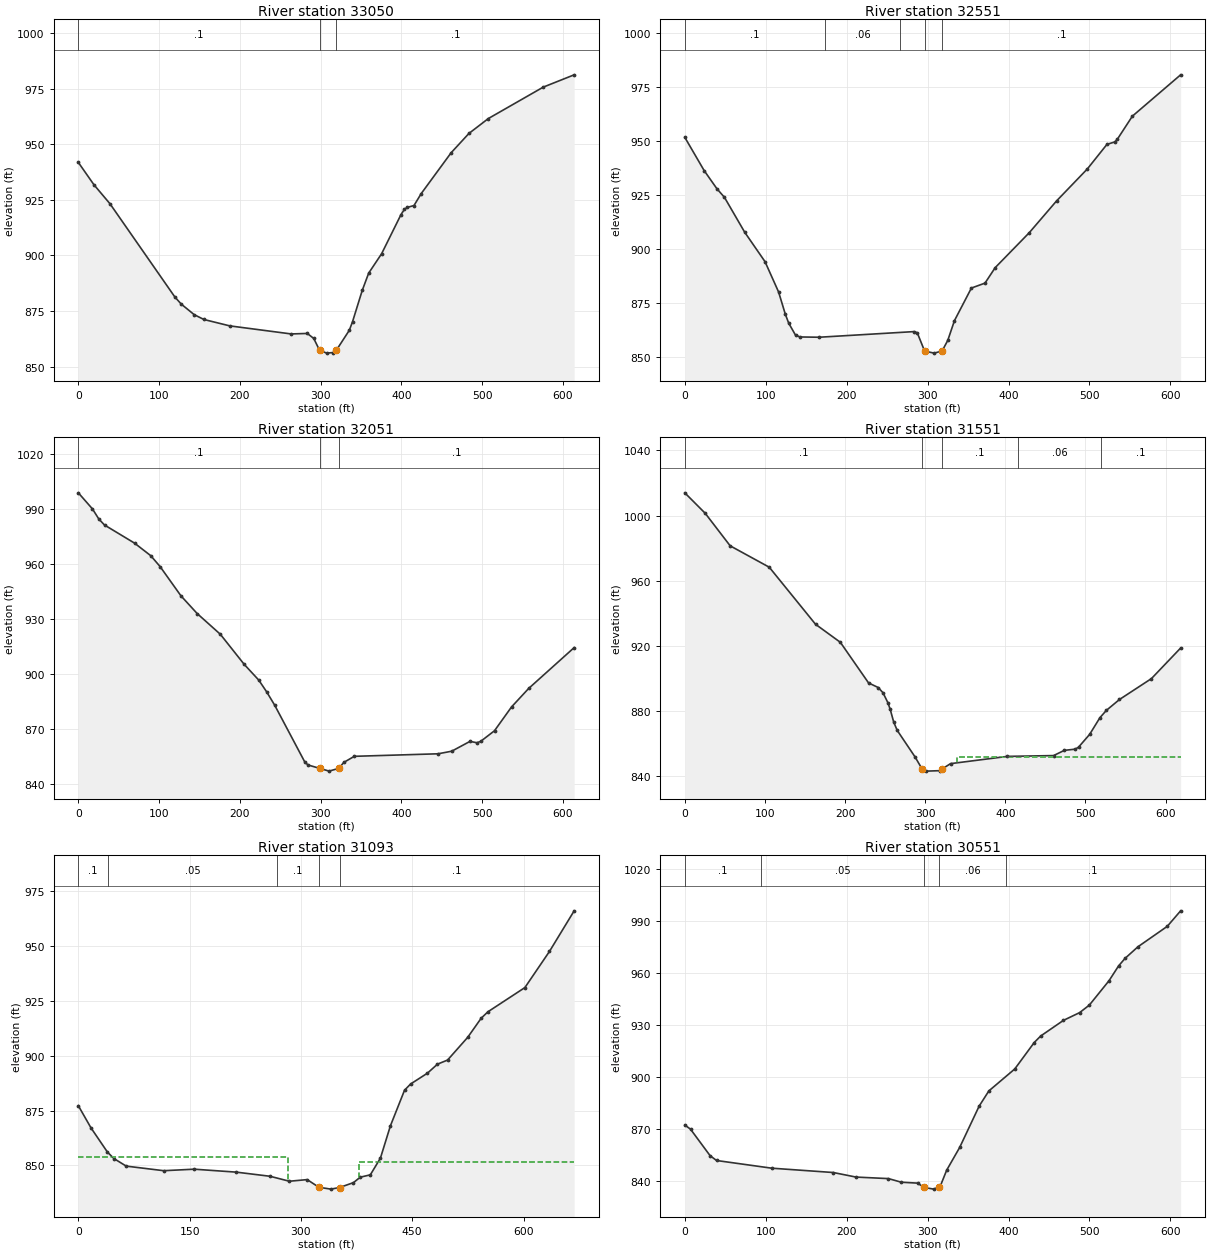
Type RM Length L Ch R = 1 ,33050   ,496.4,499.2,502.2
XS GIS Cut Line= 6
1635204.65596785364437.0854004171635299.24436134364435.067359835
1635462.25026892364433.1461038441635562.27172242364434.766179338
1635637.20398726364437.9551493381635818.40047526364441.808160007
#Sta/Elev= 30
       0  941.81    19.3  931.79    39.2  923.23   119.5  881.36   127.5  878.13
   143.5   873.4   155.5  871.24   187.5  868.37   263.5  864.75   283.5  864.97
   291.5  862.72   298.6857.4543   307.5  856.13   315.5   856.4   319.5  857.45
   335.5  866.39   339.5  870.25   351.5  884.29   359.5  892.08   375.5  900.78
   399.5  918.37   403.7  920.69   407.2  921.58   415.6  922.45   424.6  927.84
   461.6  946.16   483.6  954.82   507.6  961.51   575.6  975.63   613.9  981.16
#Mann= 3 ,-1,0
       0      .1       0   298.6    .045       0   319.5      .1       0
Bank Sta=298.6,319.5
XS Rating Curve= 0 ,0
Exp/Cntr(USF)=0,0
Exp/Cntr=0.3,0.1

Type RM Length L Ch R = 1 ,32551   ,494,500,508.5
XS GIS Cut Line= 6
1635117.25817676 364825.854307921635290.69352542364878.502168506
1635458.14824301364929.3347440061635529.53852017364952.358320013
1635612.38087417 364980.689300091635700.94959468365011.673818171
#Sta/Elev= 30
       0  951.64    23.9  936.29    39.7  927.88      49  923.92      74  907.81
    99.1  894.22   115.9  880.19   124.2  869.93   128.4  865.79   136.8  860.26
   142.3  859.43     166   859.3   283.1   861.9   287.2  861.38   296.3852.9017
   308.1  851.96   317.9852.9438   324.9  857.84   333.2     867   354.1  882.02
   370.9   884.3   383.5  891.45   425.6  907.59   459.3  922.26   497.4  937.06
   521.6   948.4   531.2   949.5   534.2  950.64     553  961.42   612.6  980.51
#Mann= 5 ,-1,0
       0      .1       0  173.75     .06       0  266.25      .1       0
   296.3    .045       0   317.9      .1       0
Bank Sta=296.3,317.9
XS Rating Curve= 0 ,0
Exp/Cntr(USF)=0,0
Exp/Cntr=0.3,0.1

Type RM Length L Ch R = 1 ,32051   ,503.4,500,491.6
XS GIS Cut Line= 6
1634933.50460726365042.2065654991634987.39163859365118.929509178
1635038.02572368  365190.29288351635184.00738709365393.244577333
1635236.39179675365463.3490959261635304.26994184365529.985773668
#Sta/Elev= 30
       0   998.6    17.5  989.82    25.4  984.31    32.4  981.06    69.6  971.18
    89.7  964.32   101.2  958.42     127  942.48   147.1  932.81   175.8   921.5
   205.4  905.08   223.4  896.51   233.1  890.16   243.1  882.85   280.7  851.61
   284.7   850.2     299  848.38   310.5  846.89   322.5  848.42   328.7  851.65
   341.7  854.96   445.4  856.34   462.3  857.75   484.9   863.1   493.7  862.35
   498.3  863.15   515.3  868.92   536.4   881.9   557.6  891.97   613.9  914.23
#Mann= 3 ,-1,0
       0      .1       0     299    .045       0   322.5      .1       0
Bank Sta=299,322.5
XS Rating Curve= 0 ,0
Exp/Cntr(USF)=0,0
Exp/Cntr=0.3,0.1

Type RM Length L Ch R = 1 ,31551   ,484.8,458.7,436.2
XS GIS Cut Line= 6
  1634605.094831365593.6191765821634689.62353334365634.164699167
 1634836.1399726365704.4447423371634926.30383426365747.693671584
 1635072.8202735365817.9730585961635172.28890659365827.617724344
#Sta/Elev= 30
       0 1013.94    25.5 1001.38    56.6  981.44   105.4  968.32   163.1  933.35
   194.1  922.27   229.3  897.36   241.3  894.55   247.3  891.35   253.3  885.35
   256.3  881.19   260.7  873.32   265.1  868.22   287.3  851.99   296.3844.4028
   301.3  843.27   318.3  843.55   320.6 844.455   331.6  847.86   402.6  852.31
   460.2   852.8   473.6  856.01   487.2  856.74   491.3  857.96   505.2  865.82
     518  876.05   526.1  880.55   542.4   887.2   582.3  900.02   618.7  918.76
#Mann= 5 ,-1,0
       0      .1       0   296.3    .045       0   320.6      .1       0
  416.25     .06       0  518.75      .1       0
#XS Ineff= 2 , 0
                          339.75           852.2
Permanent Ineff=
       F       F
Bank Sta=296.3,320.6
XS Rating Curve= 0 ,0
Exp/Cntr(USF)=0,0
Exp/Cntr=0.3,0.1

Type RM Length L Ch R = 1 ,31093   ,518.6,541.3,554.4
XS GIS Cut Line= 6
1634740.73760433366315.3549378371634833.79483293366270.416051343
1634916.79794776366224.7278225121634988.13710248366176.962500801
1634986.27542548366096.7267824731635254.77332167365954.069899261
#Sta/Elev= 30
       0  877.19    17.1  867.09    39.3  856.06    48.2  853.11    64.5  849.72
   115.1  847.63   156.2  848.32   212.8  846.98   258.3   845.1   284.4  842.84
   308.4  843.58   324.2840.0955   340.4  839.25   352.1839.9895   370.8  842.21
   379.9  844.68   393.5  845.75   407.1  853.34   420.6  868.07   439.6  884.24
   447.8  887.07   470.5     892     484  896.09   497.6  897.96   524.8  908.32
   542.9  916.99     552  919.92   601.8  930.93   634.9  947.36   668.2  965.84
#Mann= 5 ,-1,0
       0      .1       0      40     .05       0  268.09      .1       0
   324.2    .045       0   352.1      .1       0
#XS Ineff= 2 , 0
          283.13  854.08  378.49          851.79
Permanent Ineff=
       F       F
Bank Sta=324.2,352.1
XS Rating Curve= 0 ,0
Exp/Cntr(USF)=0,0
Exp/Cntr=0.3,0.1

Type RM Length L Ch R = 1 ,30551   ,377,371.6,367.6
XS GIS Cut Line= 6
1634780.97932176366650.9622062591634874.56870151366645.281115249
  1634961.928763366640.1984482561635036.82985993366636.312301174
1635299.06719634   366624.5715111635392.55618259366617.103350088
#Sta/Elev= 30
       0  872.18     7.1  869.75    31.2  854.48    39.2  851.66   107.3  847.22
   183.5  844.71   211.5  842.08   251.6  841.19   267.6   839.1   287.6  838.58
   295.6  836.09   307.6  835.11   314.2836.1216   315.6  836.77   323.6  846.11
   339.6  859.19   363.7  883.12   375.7   891.9   407.7  904.58   431.7  919.85
   439.7  923.62   467.8  932.66   487.8  937.14   499.8  941.48   524.2  955.63
   535.9  964.11   543.9  968.49   559.9  975.22   596.1  987.02   612.6  995.99
#Mann= 5 ,-1,0
       0      .1       0   93.76     .05       0   295.6    .045       0
   314.2     .06       0  396.27      .1       0
Bank Sta=295.6,314.2
XS Rating Curve= 0 ,0
Exp/Cntr(USF)=0,0
Exp/Cntr=0.3,0.1

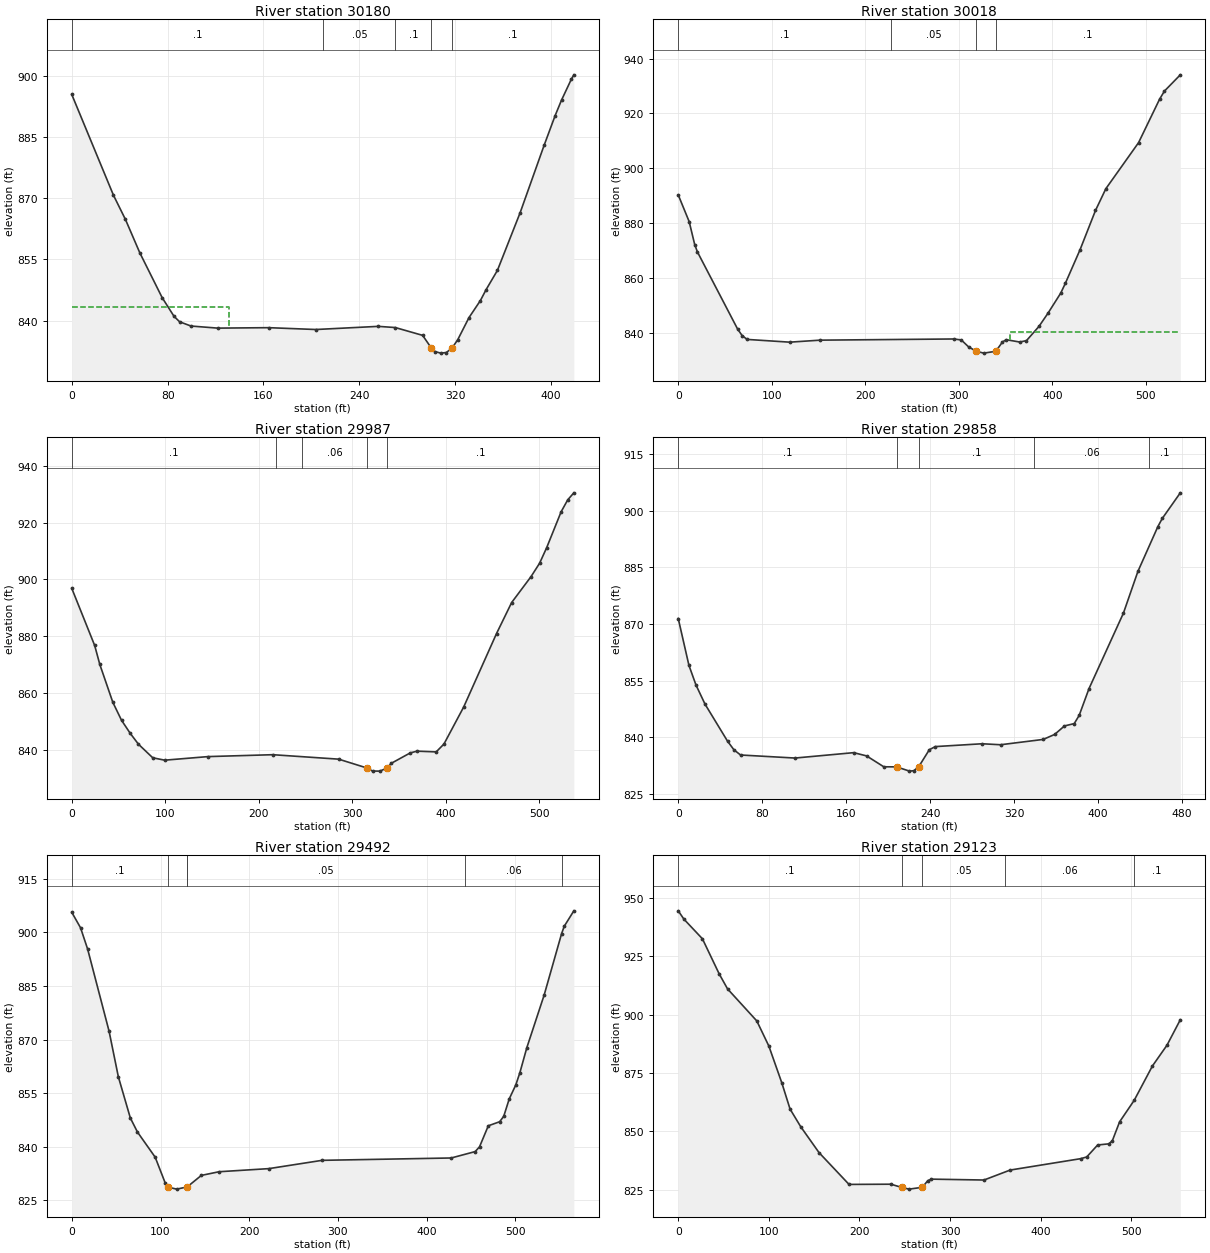
Type RM Length L Ch R = 1 ,30180   ,154.7,161.5,166.9
XS GIS Cut Line= 2
1634944.10572671367148.5492786851635297.96535467366924.200235022
#Sta/Elev= 30
       0  895.38    34.8  870.72    44.8  864.79    56.8  856.62    75.4  845.68
    85.3   841.1      90  839.75    99.5  838.71   121.8   838.2   164.4  838.31
   203.7  837.86   255.8  838.63     270  838.34   292.8  836.43   300.1833.3134
   303.1  832.46   307.9  832.08   312.6  832.23   317.3   833.3   322.1  835.36
   331.5  840.78     341  844.94   345.8  847.63   355.2  852.32   374.2  866.46
   394.2  882.95   403.4  890.22   408.7  893.99   416.8  899.05     419  900.19
#Mann= 5 ,-1,0
       0      .1       0     210     .05       0     270      .1       0
   300.1    .045       0   317.3      .1       0
#XS Ineff= 2 , 0
          131.11  843.41
Permanent Ineff=
       F       F
Bank Sta=300.1,317.3
XS Rating Curve= 0 ,0
Exp/Cntr(USF)=0,0
Exp/Cntr=0.3,0.1

Type RM Length L Ch R = 1 ,30018   ,30.5,30.7,30.7
XS GIS Cut Line= 6
1634977.10554701367197.5661860821635156.80924287367093.028950279
1635190.54972565367111.6579839351635229.86787111367126.348105214
1635300.87342211367129.1314193181635454.84640679 367040.99766626
#Sta/Elev= 30
       0  890.37    11.7  880.64    17.6  872.32    20.5  869.63    63.6  841.48
    68.3   839.2    73.6  837.78   119.2  836.78   151.6  837.51   294.7  837.94
   302.7  837.58   310.7     835   318.8833.4788   326.7  832.79   339.6833.4527
   346.7  836.84   350.7  837.68   365.2  836.83   372.4  837.34   385.7  842.49
   395.5  847.37     409  854.62   413.9  858.14   429.7  870.43   446.2  884.71
   457.3  892.64   492.3  909.41   514.7  925.18   519.9  928.15   536.9  934.07
#Mann= 4 ,-1,0
       0      .1       0   227.9     .05       0   318.8    .045       0
   339.6      .1       0
#XS Ineff= 2 , 0
                          354.86          840.49
Permanent Ineff=
       F       F
Bank Sta=318.8,339.6
XS Rating Curve= 0 ,0
Exp/Cntr(USF)=0,0
Exp/Cntr=0.3,0.1

Type RM Length L Ch R = 1 ,29987   ,126.6,129.3,130.4
XS GIS Cut Line= 6
1634982.15167294367228.099520793 1635161.8553688 367123.56228499
1635195.59585158367142.1913186471635234.91399704367156.881439926
1635305.91954804 367159.664754031635459.89253272367071.531000972
#Sta/Elev= 30
       0   896.8    24.5  876.66      30  869.97    43.9  856.64    53.2  850.31
    62.6  845.66    71.3  841.87    86.6  837.08    99.4  836.24   145.7   837.5
     215  838.17   285.4   836.6   315.4833.5104   321.6  832.41   329.6  832.38
   337.3833.5317   341.7  835.14     362  838.81   369.2  839.42   389.7  839.16
     398  841.93   419.1  854.98   454.2  880.86   470.4  891.81   491.1  900.93
   500.3  905.67   507.9  911.18   523.3  923.79   530.4  928.02   536.9  930.47
#Mann= 5 ,-1,0
       0      .1       0   217.9     .05       0  246.44     .06       0
   315.4    .045       0   337.3      .1       0
Bank Sta=315.4,337.3
XS Rating Curve= 0 ,0
Exp/Cntr(USF)=0,0
Exp/Cntr=0.3,0.1

Type RM Length L Ch R = 1 ,29858   ,366,366.2,360.4
XS GIS Cut Line= 4
1635057.19804009367334.9629386011635206.79806148 367273.47090527
1635311.42629729367296.4156938261635490.39564803367187.198500298
#Sta/Elev= 30
       0  871.46    10.2  859.03    16.9  853.83    25.5  848.76      47  838.91
    53.1  836.62    59.4  835.25   111.3  834.44   167.2  835.87   179.5  835.01
   195.9  832.12   208.1   832.1   220.4  830.97   224.5  831.08   229.2  832.14
   239.3  836.65     245  837.48   289.6  838.23   307.2  837.97   347.8  839.38
   358.7   840.7   368.1  842.96   377.4  843.58   382.1  845.75   391.5  852.88
   424.3   872.9   438.1  883.97   457.1  895.84   461.3  898.01   478.5  904.81
#Mann= 5 ,-1,0
       0      .1       0   208.1    .045       0   229.2      .1       0
  338.86     .06       0  448.86      .1       0
Bank Sta=208.1,229.2
XS Rating Curve= 0 ,0
Exp/Cntr(USF)=0,0
Exp/Cntr=0.3,0.1

Type RM Length L Ch R = 1 ,29492   ,363.8,368.7,370.3
XS GIS Cut Line= 3
1635046.18454158367624.985065954 1635328.8643366367614.889358989
1635577.58584455367749.804715701
#Sta/Elev= 30
       0  905.63     9.9  901.29    17.9  895.31      42  872.38    52.5  859.57
      66  848.05      74  844.12      94  837.07   105.3  829.85     108828.7124
   118.2  828.13     130  828.73     146  831.97     166     833   222.1  833.87
   282.1  836.19   427.6  836.85   454.6  838.64   459.5  839.97   469.4  845.86
   482.2     847   486.8  848.52     493   853.4   500.4  857.31     505  860.74
   512.8  867.72   532.3  882.43     552  899.65     555  901.73   565.8  906.04
#Mann= 6 ,-1,0
       0      .1       0     108    .045       0     130      .1       0
     130     .05       0  442.86     .06       0  552.86      .1       0
Bank Sta=108,130
XS Rating Curve= 0 ,0
Exp/Cntr(USF)=0,0
Exp/Cntr=0.3,0.1

Type RM Length L Ch R = 1 ,29123   ,536.4,541.9,541.5
XS GIS Cut Line= 4
1634936.96919758367879.1380030841635067.28965207367954.221449637
1635272.81984318368008.3989812021635462.63527479368030.558942583
#Sta/Elev= 30
       0  944.44     6.3  940.86    26.7  932.45    45.2  917.41    54.4     911
    86.7  897.26     100   886.5   114.4  870.62   123.4   859.5   135.1  851.97
   155.4  840.82   188.5   827.2   234.8  827.29   246.4  825.93   254.7  825.18
   269.3  825.95   275.4   828.8   279.5  829.46   337.4  829.08   366.3  833.35
   444.1  838.23   450.8  838.96   462.9   844.1     475  844.58     479  845.83
   487.1  854.01   503.2  863.23   523.3  877.94   539.4  886.86   554.1  897.77
#Mann= 5 ,-1,0
       0      .1       0   246.4    .045       0   269.3     .05       0
   360.4     .06       0  502.95      .1       0
Bank Sta=246.4,269.3
XS Rating Curve= 0 ,0
Exp/Cntr(USF)=0,0
Exp/Cntr=0.3,0.1