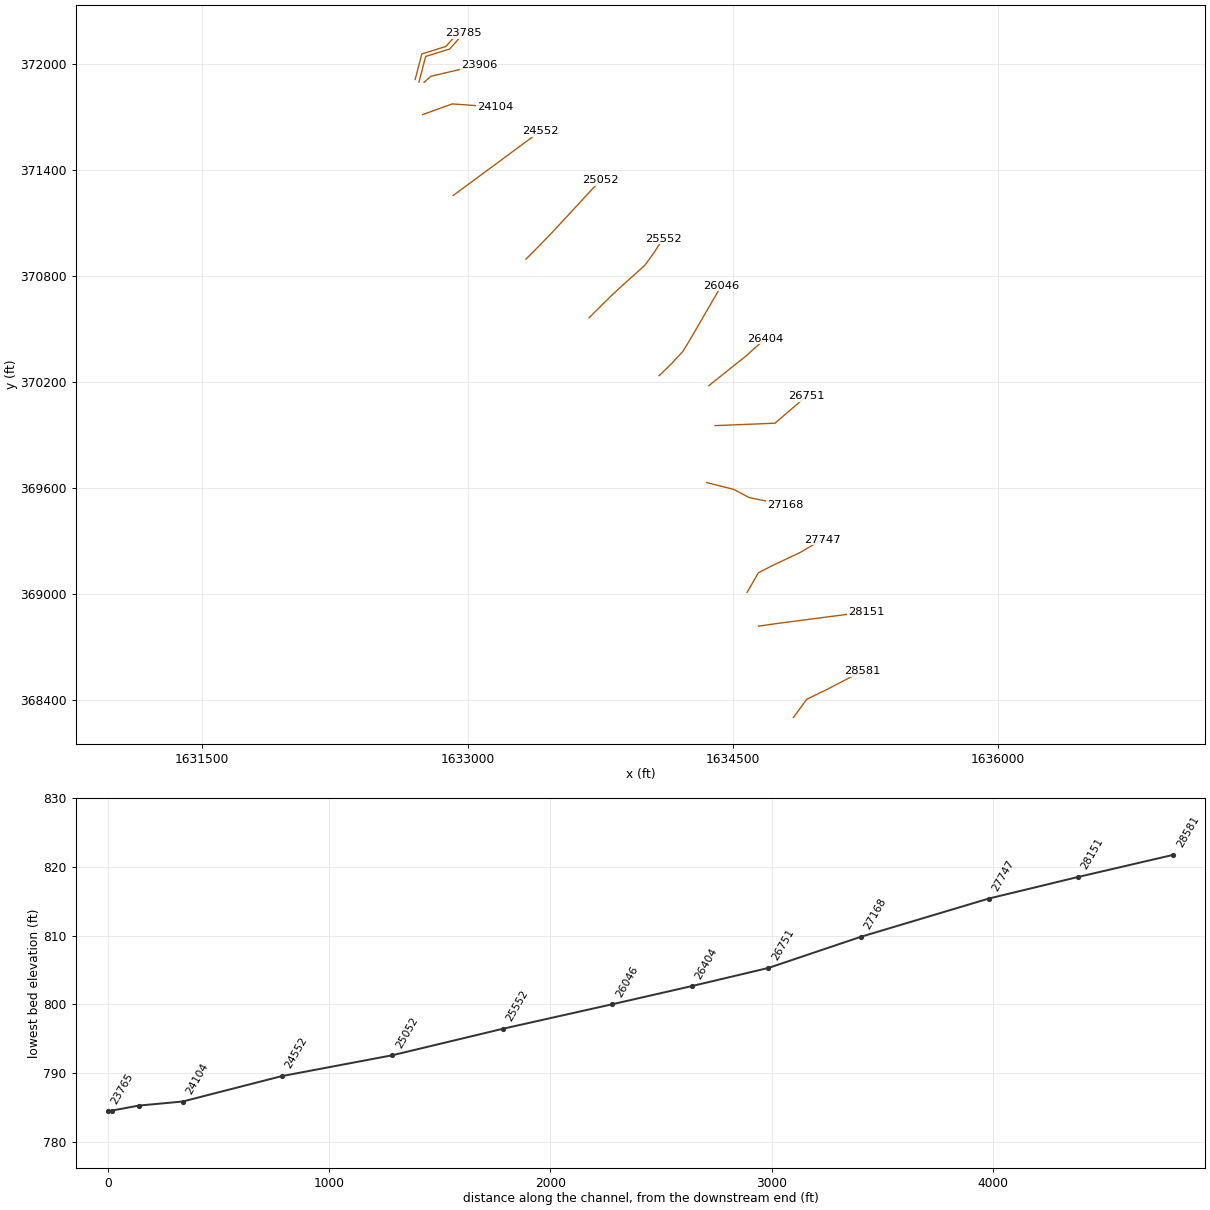
HEC-RAS study PINEYFK.prj: PINEYFK

--- PINEYFK.g01 (geometry) --- (continued)

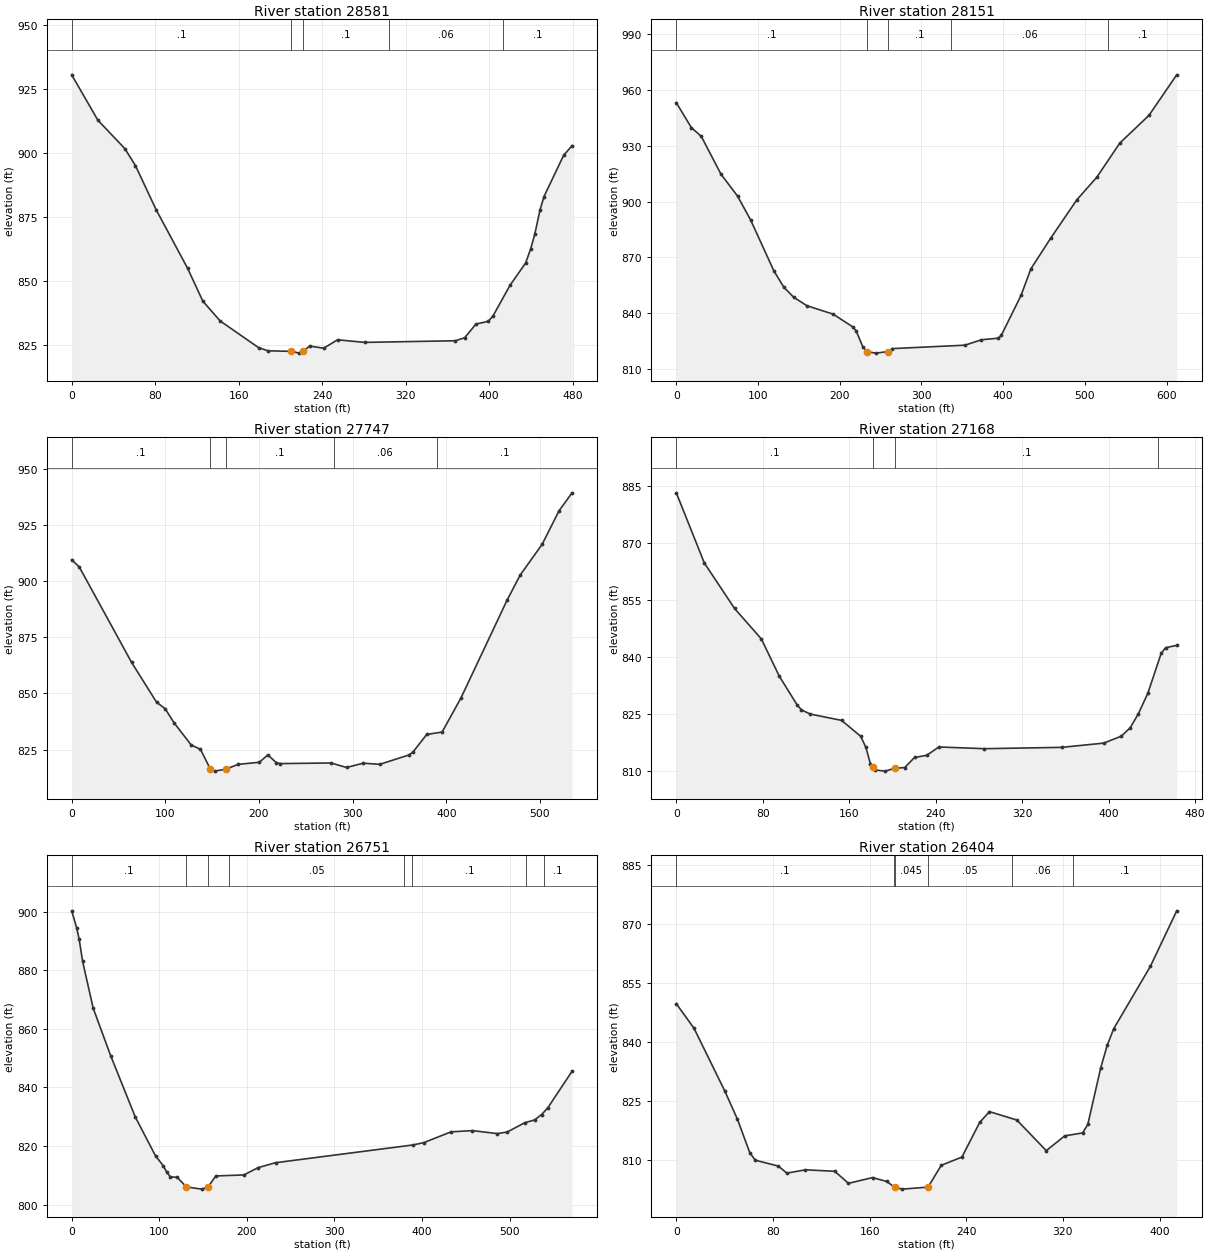
Type RM Length L Ch R = 1 ,28581   ,431.5,430,426.3
XS GIS Cut Line= 4
1634842.32066251368303.2443431681634917.73859424368406.200856216
1635031.14626459368461.1082657251635231.28629026 368565.58604494
#Sta/Elev= 30
       0  930.63    25.1  912.88    50.9  901.78    61.1  895.12    80.9  877.88
     111  854.99   125.6  842.14   142.2  834.38   179.1  823.91   188.1  822.69
   210.3  822.48     218  821.78   221.7822.4498     228  824.56   241.4  823.69
   254.7     827   280.6  825.98   367.5  826.62   376.5   827.8   387.3  833.16
   399.1  834.22   403.6  836.29   419.9  848.29   434.8  856.98   439.7  862.51
   443.7  868.38   448.7  877.84   452.5  883.04   471.3  899.15   479.4  902.93
#Mann= 5 ,-1,0
       0      .1       0   210.3    .045       0   221.7      .1       0
  303.62     .06       0  413.62      .1       0
Bank Sta=210.3,221.7
XS Rating Curve= 0 ,0
Exp/Cntr(USF)=0,0
Exp/Cntr=0.3,0.1

Type RM Length L Ch R = 1 ,28151   ,400.1,404.7,410.2
XS GIS Cut Line= 6
1634645.95265885368819.5531470641634738.72150218368833.163027988
1634825.48642051368844.4805906581634999.01658526368867.115059824
1635073.38651526368876.8151716451635253.11417419368900.258366228
#Sta/Elev= 30
       0  953.15    18.4  939.77    30.5   935.1    54.7  914.71      75  902.92
    90.9  890.17   119.4  862.79   131.5  854.04   143.6  848.62   159.7  844.07
     192   839.5   216.2   832.6   220.2  830.42   228.3  821.97   233.1819.3673
   244.4  818.56   258.5  819.38   264.6     821   353.3  822.83   373.5  825.74
   394.2  826.59   397.8  828.13   421.9  849.53     434  863.86   458.2  880.31
   490.5  901.09   514.7   913.1   542.9  931.47   578.6  946.37   612.5  968.12
#Mann= 5 ,-1,0
       0      .1       0   233.1    .045       0   258.5      .1       0
  336.26     .06       0  528.76      .1       0
Bank Sta=233.1,258.5
XS Rating Curve= 0 ,0
Exp/Cntr(USF)=0,0
Exp/Cntr=0.3,0.1

Type RM Length L Ch R = 1 ,27747   ,588.7,578.3,570.6
XS GIS Cut Line= 5
1634580.07107351 369010.065794641634644.69820637369121.859301241
1634716.26827007369158.5981488111634879.67382517 369235.87688852
1635004.09828539369308.266861536
#Sta/Elev= 30
       0  909.47     8.1  906.29      64  863.77    90.6   846.1    99.9  843.15
   109.1  837.03   127.7  827.01   137.5  825.14     148816.3475   152.5  815.41
   164.5816.2769   177.9  818.43   200.4  819.35   209.4  822.64   218.3  819.24
   222.7  818.76     277  819.04   293.5  817.03   311.2  818.94   328.9  818.43
   359.9  822.57   364.3  823.85   379.1  831.74   395.5   832.8   415.5  847.86
   464.9   891.5   478.9  902.69   502.3  916.34   520.4  931.31   534.3  939.27
#Mann= 5 ,-1,0
       0      .1       0     148    .045       0   164.5      .1       0
  279.58     .06       0  389.58      .1       0
Bank Sta=148,164.5
XS Rating Curve= 0 ,0
Exp/Cntr(USF)=0,0
Exp/Cntr=0.3,0.1

Type RM Length L Ch R = 1 ,27168   ,406.9,417.1,418.7
XS GIS Cut Line= 4
1634351.87391549369631.8116284681634505.07960707369592.897271407
1634591.54867564369547.0176876761634794.18900998369504.765376172
#Sta/Elev= 30
       0  883.13    25.9  864.67    53.9  852.67    78.7  844.65    95.2  834.88
   111.7  827.31   115.8  825.95   124.1  824.85   152.9  823.21   170.6  819.01
   175.4   816.1   179.6  811.76   182.1810.7972   184.2  810.13   193.2  809.84
   202.3   810.6   211.3  810.78   220.4  813.43   231.6     814     243   816.2
   285.1  815.75   356.7   816.1   395.5  817.22   411.8  819.05     420  821.28
   427.6  824.99   436.3  830.37   448.6  840.83   452.7  842.34     463  842.96
#Mann= 4 ,-1,0
       0      .1       0   182.1    .045       0   202.3      .1       0
  445.96     .06       0
Bank Sta=182.1,202.3
XS Rating Curve= 0 ,0
Exp/Cntr(USF)=0,0
Exp/Cntr=0.3,0.1

Type RM Length L Ch R = 1 ,26751   ,337,347.6,353.9
XS GIS Cut Line= 3
1634399.63018799369953.4056244041634738.29526708369967.172497538
 1634914.5112432370118.608102011
#Sta/Elev= 30
       0  900.28     5.6  894.58     8.5  890.63    12.5  883.02    24.5  867.09
    44.5  850.85    72.5     830    95.8  816.61   104.6  813.26   108.6  811.04
   112.6  809.54   120.6   809.3     131 806.052   148.6  805.31   155.7 806.052
   164.6  809.81   196.6  810.15   212.7  812.63   232.7  814.32   390.1   820.4
   402.4  821.22   433.1  824.86   457.5  825.28   485.9  824.26   497.2  824.79
   517.1  827.96   528.4  828.91   536.5  830.76   543.6  833.07   571.3  845.56
#Mann= 8 ,-1,0
       0      .1       0     131    .045       0   155.7      .1       0
     180     .05       0  378.94     .06       0  388.94      .1       0
  518.94     .07       0  538.94      .1       0
Bank Sta=131,155.7
XS Rating Curve= 0 ,0
Exp/Cntr(USF)=0,0
Exp/Cntr=0.3,0.1

Type RM Length L Ch R = 1 ,26404   ,346.3,357.3,357.5
XS GIS Cut Line= 3
1634364.62762413370179.7425807111634574.01058102370347.138196032
1634683.02899327370444.403697768
#Sta/Elev= 30
       0  849.69    14.7  843.44    40.3  827.44    50.6  820.39    60.8  811.92
    65.3     810    84.5   808.5    91.5  806.72   106.9  807.56   131.1  807.19
   142.5  804.13   162.4  805.59   174.2   804.6   180.6  803.16     187  802.66
   208.4803.1746   219.3  808.71   236.4  810.79   251.1  819.57   259.2  822.32
   281.9  820.18   306.2  812.42   321.5  816.17   336.3  816.92   340.6  819.06
   351.3  833.44   356.7  839.16     362  843.33   392.4  859.18   414.2  873.26
#Mann= 6 ,-1,0
       0      .1       0     180     .05       0   180.6    .045       0
   208.4     .05       0  278.07     .06       0  328.07      .1       0
Bank Sta=180.6,208.4
XS Rating Curve= 0 ,0
Exp/Cntr(USF)=0,0
Exp/Cntr=0.3,0.1

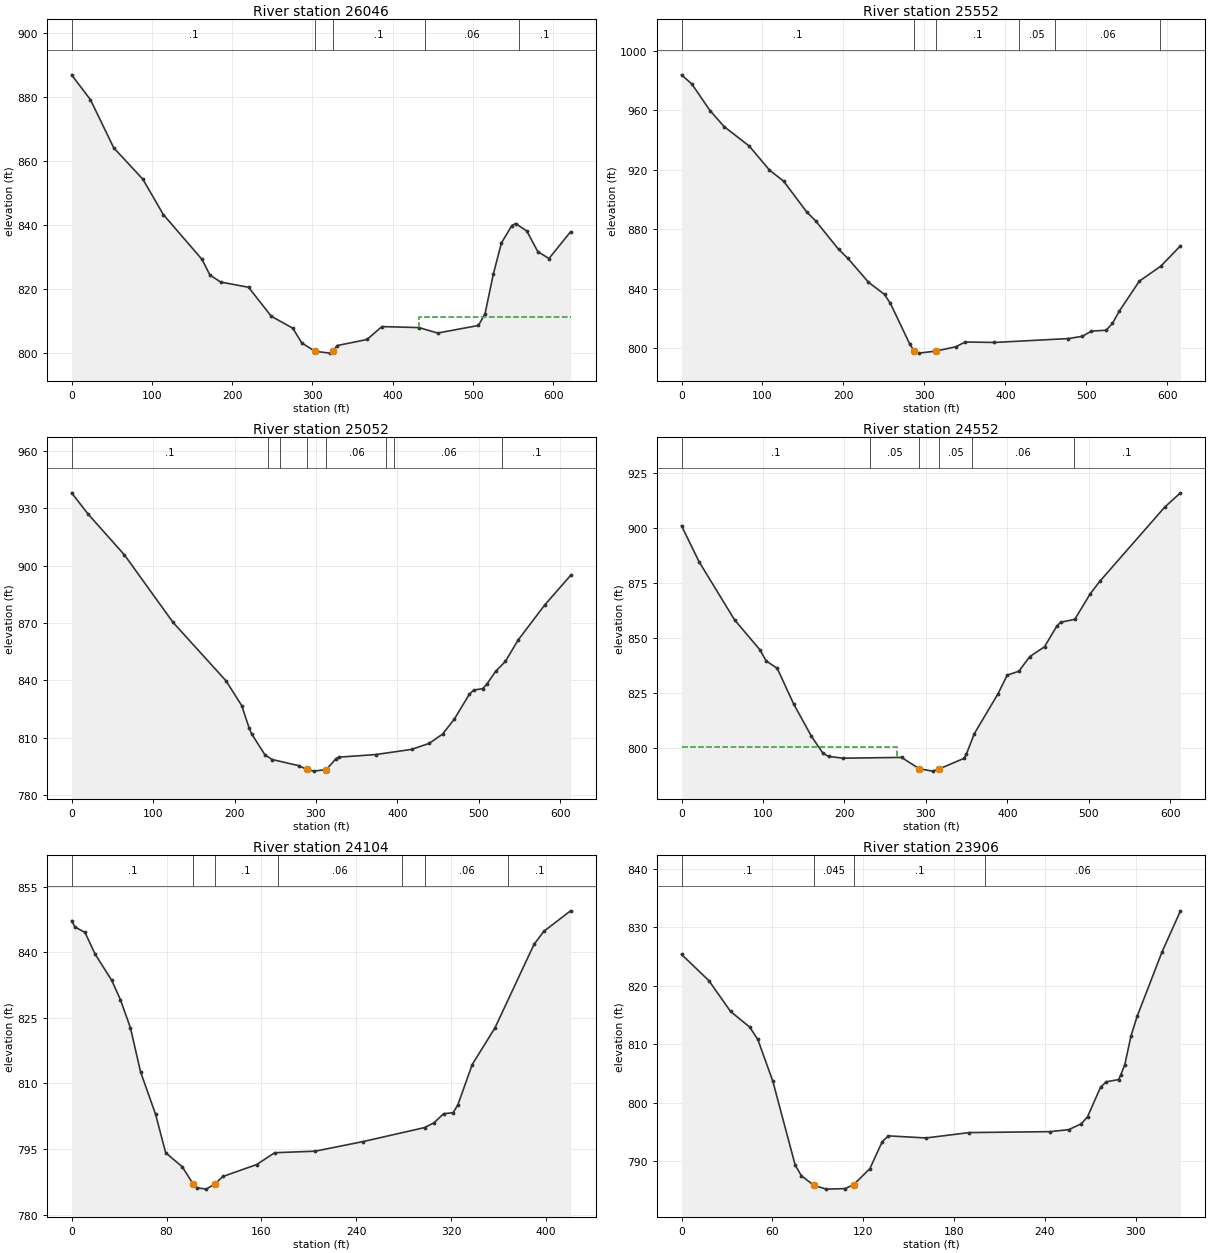
Type RM Length L Ch R = 1 ,26046   ,497.9,494.5,491
XS GIS Cut Line= 6
1634083.28222634370235.9225560131634154.01928958370304.664216429
1634216.27343017370371.8625728341634255.73004417370435.679374337
1634343.55893676370587.0432448391634434.52496217370743.812944427
#Sta/Elev= 30
       0  887.07    23.5  879.27    52.5  864.22    88.7  854.44   114.2  843.38
   162.3  829.38   172.3  824.46   185.7  822.26   220.4  820.63   248.7  811.56
   275.5  807.83   286.7  803.22   303.3  800.59   321.7  800.03   325.1800.5735
     331  802.41     368   804.3   386.5  808.33   432.7  808.02   455.9  806.31
   506.7  808.68   514.9  812.29   525.2  824.64   535.4  834.52   548.4  839.94
     553  840.57   566.9  838.25   580.7  831.78   594.6  829.62   621.5  837.99
#Mann= 5 ,-1,0
       0      .1       0   303.3    .045       0   325.1      .1       0
  440.27     .06       0  557.77      .1       0
#XS Ineff= 2 , 0
                          433.06          811.22
Permanent Ineff=
       F       F
Bank Sta=303.3,325.1
XS Rating Curve= 0 ,0
Exp/Cntr(USF)=0,0
Exp/Cntr=0.3,0.1

Type RM Length L Ch R = 1 ,25552   ,498.1,500,500.6
XS GIS Cut Line= 6
1633687.04187709370563.2007728371633816.03965059370691.263180763
1633871.22720426370742.0613075051634001.37130092370859.055824175
1634054.00144501370930.5648675111634105.03185476371011.426910505
#Sta/Elev= 30
       0  984.04    12.8  977.83    35.3  959.88    52.6  949.17    83.7  935.99
   108.5  919.93   126.2  912.29   154.4  891.77   165.8  885.49     194  866.42
   205.4  860.36   230.8  844.32   250.7     836     258  829.94   281.8  802.67
   287.5  797.77   293.2  796.46   313.9 797.816   338.5  800.72   350.5  803.97
   386.3  803.65   477.7  806.27   494.9  807.79   506.3   811.3   524.5  811.91
   532.2  816.53   540.9  825.02   565.5  845.03     592   855.1   616.2  868.79
#Mann= 6 ,-1,0
       0      .1       0   287.5    .045       0   313.9      .1       0
  416.78     .05       0  461.78     .06       0  590.57      .1       0
Bank Sta=287.5,313.9
XS Rating Curve= 0 ,0
Exp/Cntr(USF)=0,0
Exp/Cntr=0.3,0.1

Type RM Length L Ch R = 1 ,25052   ,502.2,500,497.7
XS GIS Cut Line= 6
1633329.98583268370894.4740604161633396.01686859370961.104176506
1633457.18472525371023.7182245111633508.62622343371078.301120594
1633576.51191442371151.7281390881633750.46825942371339.885899261
#Sta/Elev= 30
       0  938.15    20.1  927.11    64.9  905.67   124.6  870.36   189.7  839.77
   208.9  826.83   217.9  815.19   220.9  812.16   237.4   801.1   246.2  798.68
   279.2  795.42   288.7  793.47   297.5   792.6   312.8  793.45   324.8   799.2
   328.3  799.91   373.4  801.27   417.4  803.97   439.2  807.14   455.5  811.99
   469.9  819.82   488.2  832.74   493.6  834.99   504.5  835.73   509.5  837.92
   520.8   844.9   532.5  849.94   548.1   861.1   580.8  879.46   612.6  894.96
#Mann= 8 ,-1,0
       0      .1       0  241.34     .05       0  256.34     .06       0
   288.7    .045       0   312.8     .06       0  386.34     .07       0
  396.34     .06       0  528.84      .1       0
Bank Sta=288.7,312.8
XS Rating Curve= 0 ,0
Exp/Cntr(USF)=0,0
Exp/Cntr=0.3,0.1

Type RM Length L Ch R = 1 ,24552   ,449.8,448,445.8
XS GIS Cut Line= 6
1632918.78389917371254.7935497611632994.22666167371310.448294088
1633124.99378859371406.917261258 1633205.4660686 371466.28230001
1633336.23286742371562.7512671651633411.67628609371618.405027255
#Sta/Elev= 30
       0  901.11    21.5  884.79    65.1  858.34    96.1  844.78     104  839.62
   117.5   836.3   137.7  820.06   159.5  805.38   173.8  797.63   180.6  796.25
   198.3  795.44   270.1   795.8     292 790.605   308.3  789.56   316.2790.5446
   346.6  795.34   349.6  797.22   359.5  806.64   388.4  824.64   399.8  833.21
   414.1  834.97   427.4  841.59   445.6   846.1   461.1  855.74   465.6  857.26
   482.8  858.58   501.5  870.05   513.6  875.91   593.2   909.6   612.5  916.08
#Mann= 6 ,-1,0
       0      .1       0  231.25     .05       0     292    .045       0
   316.2     .05       0  356.25     .06       0  481.25      .1       0
#XS Ineff= 2 , 0
          264.49  800.73
Permanent Ineff=
       F       F
Bank Sta=292,316.2
XS Rating Curve= 0 ,0
Exp/Cntr(USF)=0,0
Exp/Cntr=0.3,0.1

Type RM Length L Ch R = 1 ,24104   ,197.1,198.2,197.1
XS GIS Cut Line= 4
1632745.46204226371711.9714619661632814.69607045371736.826867267
1632913.12798008371772.4987657321633154.84366609371755.131444253
#Sta/Elev= 30
       0  847.19     2.8  845.76    11.3  844.51    19.8  839.56    33.8  833.57
    41.1  829.18    49.6   822.7    58.1  812.67    70.8  802.94    79.3  794.17
    93.2  790.99   102.5  787.01   105.7  786.17   113.4  785.86   120.7787.0263
   127.5  788.75   155.9  791.46   171.2  794.18   205.3  794.53   245.4  796.71
   297.5  799.92   305.6  801.04   313.6   803.1   321.6  803.32   325.6  805.12
   337.7  814.33   356.9  822.72   389.8  841.79     398  844.75   420.6  849.45
#Mann= 7 ,-1,0
       0      .1       0   102.5    .045       0   120.7      .1       0
  173.56     .06       0  278.26      .1       0  298.26     .06       0
  368.26      .1       0
Bank Sta=102.5,120.7
XS Rating Curve= 0 ,0
Exp/Cntr(USF)=0,0
Exp/Cntr=0.3,0.1

Type RM Length L Ch R = 1 ,23906   ,118.5,120.1,120.5
XS GIS Cut Line= 3
  1632754.688068371894.8144837271632792.31752123371928.772770791
1633063.98381774371992.100387206
#Sta/Elev= 30
       0  825.37    18.1  820.88    32.4  815.62      45  812.96    50.4  810.84
    60.3  803.71    75.1  789.36    79.2  787.55    87.4  785.92    95.7  785.27
     108  785.36   113.7786.0293   124.4  788.76   132.6  793.38   136.7  794.37
   161.4  794.01   190.1  794.93   243.5  795.09   255.8  795.43   264.1  796.44
   268.2  797.63   276.8  802.67   280.5   803.6   288.7  803.98   290.1  804.75
   292.8  806.51   296.9  811.42     301   814.8   317.4  825.78   329.6  832.81
#Mann= 4 ,-1,0
       0      .1       0    87.4    .045       0   113.7      .1       0
  200.69     .06       0
Bank Sta=87.4,113.7
XS Rating Curve= 0 ,0
Exp/Cntr(USF)=0,0
Exp/Cntr=0.3,0.1

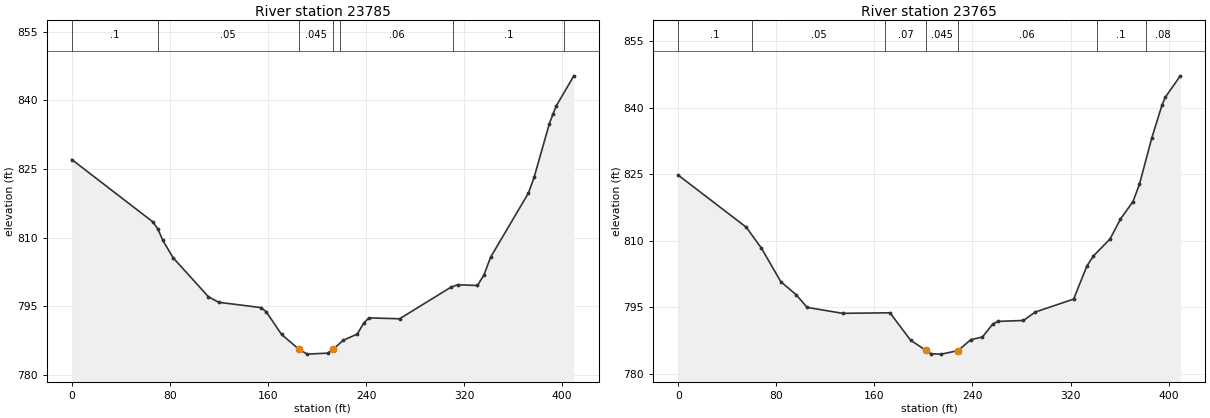
Type RM Length L Ch R = 1 ,23785   ,20,20,20
XS GIS Cut Line= 4
1632725.31873865371896.6500668121632762.94819188372040.743338946
1632898.78134013 372082.961749891632977.71141277372171.069737946
#Sta/Elev= 30
       0  827.08      66  813.48    70.2  811.92    74.3   809.4    82.6  805.63
   111.5  797.08   119.8  795.88   154.3  794.72   158.5  793.84   171.1  788.86
   185.3785.6148     192  784.55   208.8  784.77     213  785.58   221.4  787.58
   232.8  788.92   238.1  791.31   242.3  792.47   267.4  792.28   309.4   799.2
   314.8  799.71   330.9  799.55   336.2  801.86   341.6  805.73   372.5  819.77
   377.1  823.19   389.5   834.9   392.4  836.97   395.3  838.86   409.5  845.37
#Mann= 7 ,-1,0
       0      .1       0      70     .05       0   185.3    .045       0
     213      .1       0  218.93     .06       0  311.17      .1       0
  401.17     .08       0
Bank Sta=185.3,213
XS Rating Curve= 0 ,0
Exp/Cntr(USF)=0,0
Exp/Cntr=0.3,0.1

Type RM Length L Ch R = 1 ,23765   ,179.1,203,209.9
XS GIS Cut Line= 4
1632703.75063741371910.8758357171632741.38009064372054.969107851
1632877.21323889372097.1875187951632956.14331153372185.295506851
#Sta/Elev= 30
       0  824.76    55.5  813.02    67.9  808.28    83.6  800.77    96.4  797.74
   105.1  794.95     134  793.61   172.7  793.73   189.5  787.55   202.1  785.23
   206.2  784.49   214.6  784.41   228.2785.1963   238.6  787.67   248.1  788.27
   256.5  791.18   260.7  791.79   281.6     792   291.2   793.9   322.5  796.82
   333.3  804.28   338.6  806.53   352.2  810.38   360.7  814.86   370.9  818.81
   376.2  822.73   386.2  833.11   394.7  840.68   397.4  842.38   409.5  847.15
#Mann= 7 ,-1,0
       0      .1       0      60     .05       0  168.93     .07       0
   202.1    .045       0   228.2     .06       0  341.17      .1       0
  381.17     .08       0
Bank Sta=202.1,228.2
XS Rating Curve= 0 ,0
Exp/Cntr(USF)=0,0
Exp/Cntr=0.3,0.1