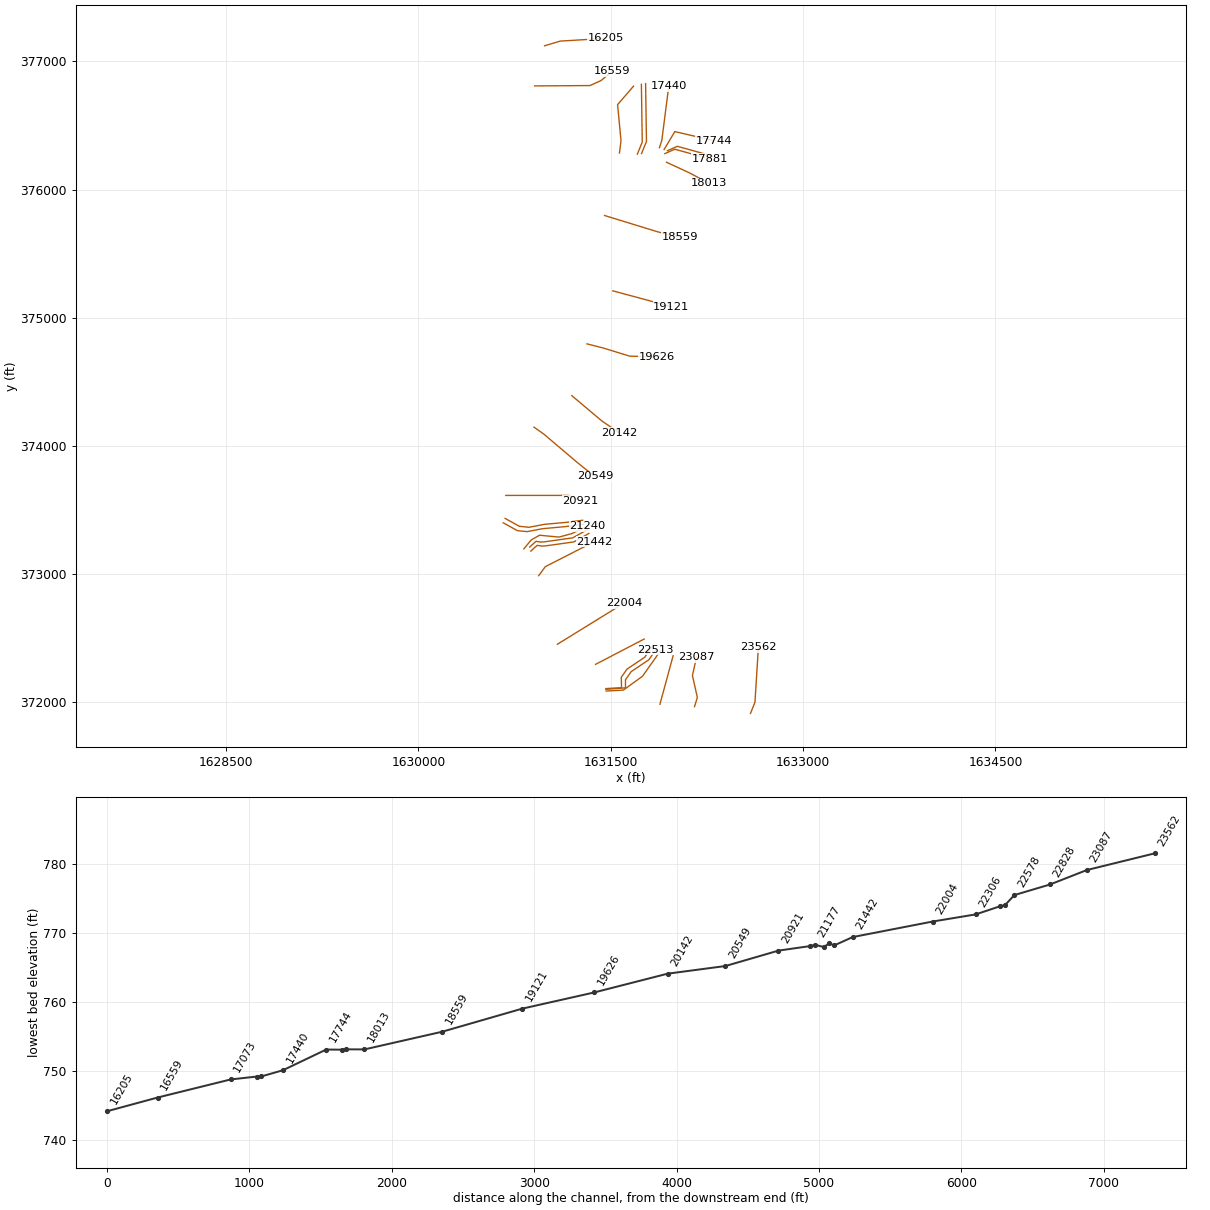
HEC-RAS study PINEYFK.prj: PINEYFK

--- PINEYFK.g01 (geometry) --- (continued)

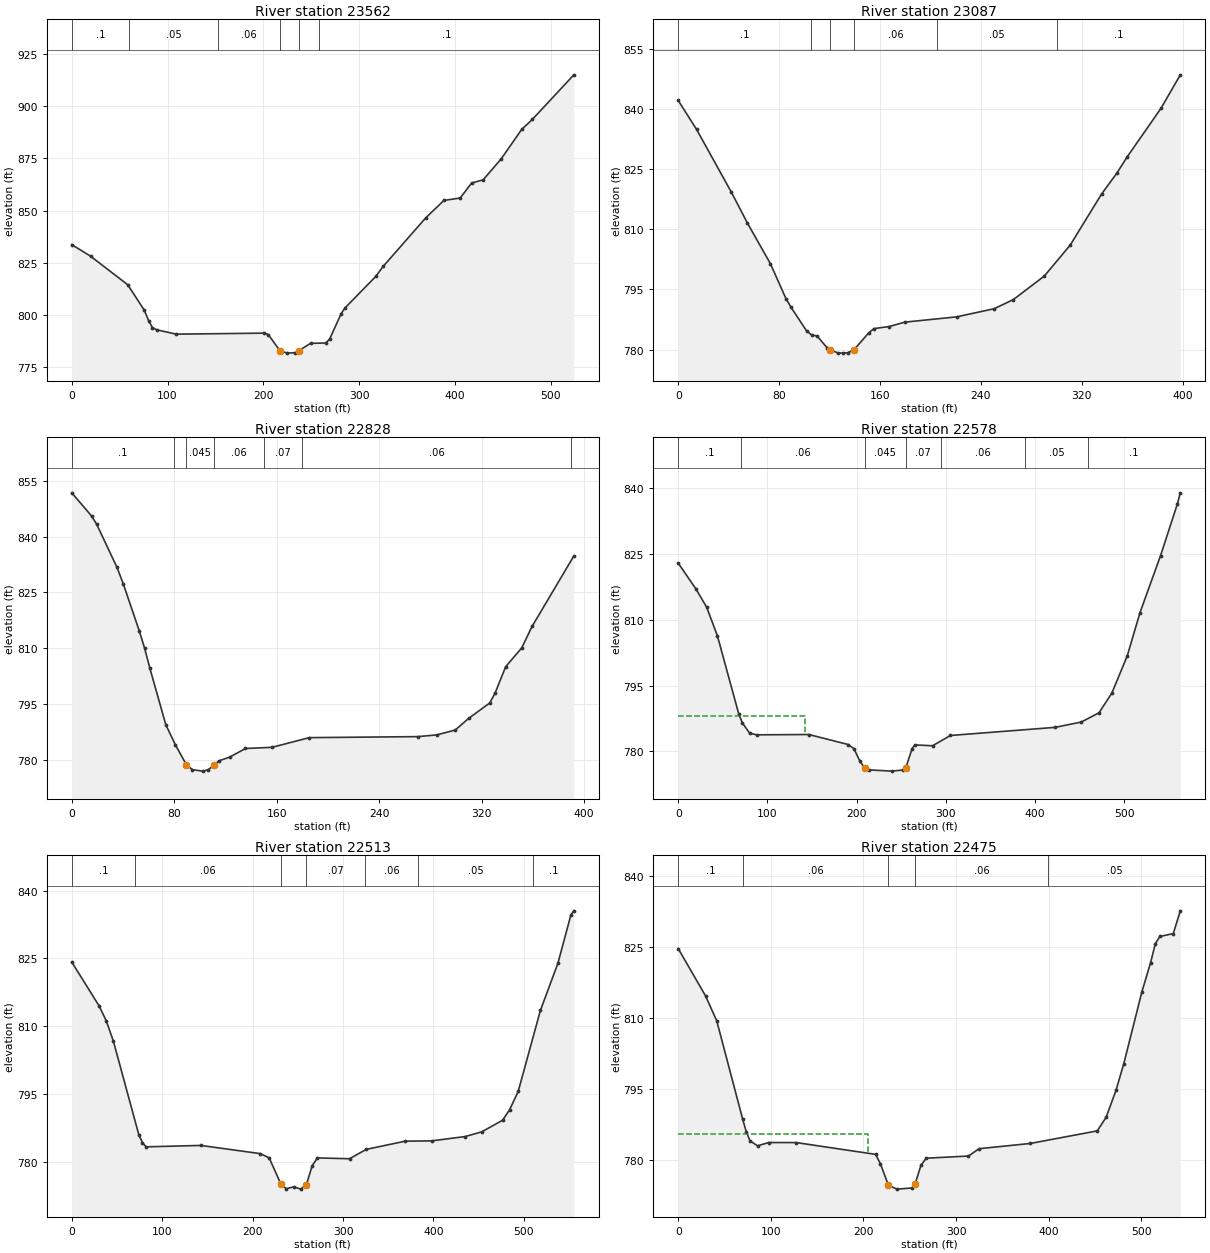
Type RM Length L Ch R = 1 ,23562   ,472.9,475.5,478.4
XS GIS Cut Line= 6
1632590.04850456371914.308850751 1632624.7679233372000.596735911
1632629.44573546372075.4505888381632640.36172413372250.109688328
 1632645.8190623372337.4392380871632651.66681964372431.006964327
#Sta/Elev= 30
       0  833.63    19.6  828.09    58.5  814.34    75.7  802.16    80.5  796.88
    84.3  793.77    88.6  792.75     109  790.64   201.2  791.13   205.2  790.45
   217.4782.6729   225.2  781.53   233.2  781.77   237.2  782.71   249.3  786.22
   265.3  786.41   269.3   788.3   281.3  800.47   285.3  803.21   317.4  818.34
   325.4  823.29   369.5  846.43   388.6  854.86   405.6  856.01   417.6  863.23
   429.6  864.74   448.5  874.87   469.8  888.94   480.9  893.73   524.3  915.18
#Mann= 6 ,-1,0
       0      .1       0      60     .05       0  153.01     .06       0
   217.4    .045       0   237.2     .06       0  258.01      .1       0
Bank Sta=217.4,237.2
XS Rating Curve= 0 ,0
Exp/Cntr(USF)=0,0
Exp/Cntr=0.3,0.1

Type RM Length L Ch R = 1 ,23087   ,262.8,258.7,252.5
XS GIS Cut Line= 5
1632153.40761963371966.6328758411632175.49164275372038.885869711
1632153.54024308372136.4470262961632137.07702141 372209.61748363
1632169.26603711372353.722113334
#Sta/Elev= 30
       0  842.14    14.5  834.94    42.1  819.29    54.9  811.55    73.1  801.43
    85.4  792.74    89.5  790.53   101.8  784.66   105.9  783.63     110  783.42
   118.2  780.41   120.6 779.989   126.4  779.19   130.5  779.12   134.6  779.22
   139.5779.9939     151  784.14   155.1  785.23   167.4  785.76   179.7  786.85
   220.7  788.16   250.6   790.2   265.8  792.48   290.4  798.36   310.9  806.08
   335.9  818.88   347.8  823.98   355.9     828   382.9   840.2   398.2  848.54
#Mann= 6 ,-1,0
       0      .1       0  105.55     .06       0   120.6    .045       0
   139.5     .06       0  205.55     .05       0  300.55      .1       0
Bank Sta=120.6,139.5
XS Rating Curve= 0 ,0
Exp/Cntr(USF)=0,0
Exp/Cntr=0.3,0.1

Type RM Length L Ch R = 1 ,22828   ,265.7,249.8,233.7
XS GIS Cut Line= 2
 1631883.7038944371985.6758464111631986.49654713 372363.80596182
#Sta/Elev= 30
       0  851.74    15.4  845.54    19.5  843.26    35.3  831.73    40.3  827.21
    52.7  814.66    56.9  809.97      61  804.59    73.4   789.5    80.9  784.07
    89.4778.7853    94.2   777.4   102.4  777.03   106.6  777.42   111.4778.7426
   114.9   779.8   123.2  780.78   135.6  783.11   156.3  783.42   185.4  786.02
   269.9  786.29   284.8  786.75   299.3  788.05   309.7  791.16   326.3  795.34
   330.4  797.96   338.7  805.07   351.2   810.1   359.4  815.94   391.9  834.79
#Mann= 7 ,-1,0
       0      .1       0      80     .06       0    89.4    .045       0
   111.4     .06       0     150     .07       0     180     .06       0
     390      .1       0
Bank Sta=89.4,111.4
XS Rating Curve= 0 ,0
Exp/Cntr(USF)=0,0
Exp/Cntr=0.3,0.1

Type RM Length L Ch R = 1 ,22578   ,60.6,65.4,72.3
XS GIS Cut Line= 4
1631464.27315959372088.4684991431631598.27072476372095.810831481
1631747.87074615372204.1102334681631888.29285211372403.270998137
#Sta/Elev= 30
       0  822.88    19.9  816.98    31.9  812.82    43.9  806.32    67.9  788.47
    71.9  786.48      80  784.14      88  783.77   146.4  783.84   190.5  781.56
   196.8  780.63   203.7  777.72   208.8776.2743   213.4  775.79   239.2   775.5
   251.4  775.75     255  776.27   262.1  780.64     265  781.47     285  781.28
     305  783.62   422.2  785.47   451.6  786.68   471.5  788.79   485.9  793.29
   503.1  801.73   517.4  811.59   540.4  824.56   559.2  836.29   562.6   838.9
#Mann= 7 ,-1,0
       0      .1       0      70     .06       0   208.8    .045       0
     255     .07       0   294.2     .06       0  388.88     .05       0
  458.88      .1       0
#XS Ineff= 2 , 0
          141.56  788.01
Permanent Ineff=
       F       F
Bank Sta=208.8,255
XS Rating Curve= 0 ,0
Exp/Cntr(USF)=0,0
Exp/Cntr=0.3,0.1

Type RM Length L Ch R = 1 ,22513   ,38.4,38.3,38.5
XS GIS Cut Line= 6
1631462.11554827372101.8601231441631614.81927098372113.498230554
1631614.83228379372176.3918622141631659.71268021372240.190272605
1631797.72675809372332.7510395051631850.94089051372411.222995415
#Sta/Elev= 30
       0  824.21    30.1  814.56    38.1  811.26    46.1  806.68    74.2  786.04
    78.2  784.32    82.2   783.4   142.6  783.71   208.2  781.91   218.3  780.97
   231.5  775.09   237.2  774.15   245.8  774.57   253.1  774.06   259.5775.0269
   265.9  779.24   271.7  780.95   307.2  780.77   325.7  782.84   368.8  784.65
   398.3  784.72     435  785.67   453.4  786.71   476.5  789.27   484.4  791.64
   493.8  795.67   518.3  813.52   537.6  823.89   552.1  834.66   555.3  835.52
#Mann= 7 ,-1,0
       0      .1       0      70     .06       0   231.5    .045       0
   259.5     .07       0   324.1     .06       0  382.81     .05       0
  510.51      .1       0
Bank Sta=231.5,259.5
XS Rating Curve= 0 ,0
Exp/Cntr(USF)=0,0
Exp/Cntr=0.3,0.1

Type RM Length L Ch R = 1 ,22475   ,174.6,168.5,162.4
XS GIS Cut Line= 6
1631462.59671234372107.7085602651631584.09552261372114.757709964
1631582.27295234372196.0071724691631627.15334876 372259.80558286
1631765.16742664 372352.366349761631818.38155906 372430.83830567
#Sta/Elev= 30
       0  824.65    29.6  814.63    41.6  809.39    69.6  788.64    73.6  785.89
    77.6  784.05    85.7     783    97.7   783.7   127.5  783.69   213.2   781.2
   218.4  779.21   227.1  774.64   236.3  773.86   252.6   774.1   255.7 774.868
   262.2   778.9   267.9  780.39   313.5  780.85     325   782.4   380.1   783.5
   452.6  786.16   462.2  789.04   472.8   794.7   481.2  800.31   500.8  815.52
   510.2   821.7   515.3  825.68   520.2  827.21   534.7  827.83   542.3  832.63
#Mann= 5 ,-1,0
       0      .1       0      70     .06       0   227.1    .045       0
   255.7     .06       0  399.77     .05       0
#XS Ineff= 2 , 0
          204.98   785.6
Permanent Ineff=
       F       F
Bank Sta=227.1,255.7
XS Rating Curve= 0 ,0
Exp/Cntr(USF)=0,0
Exp/Cntr=0.3,0.1

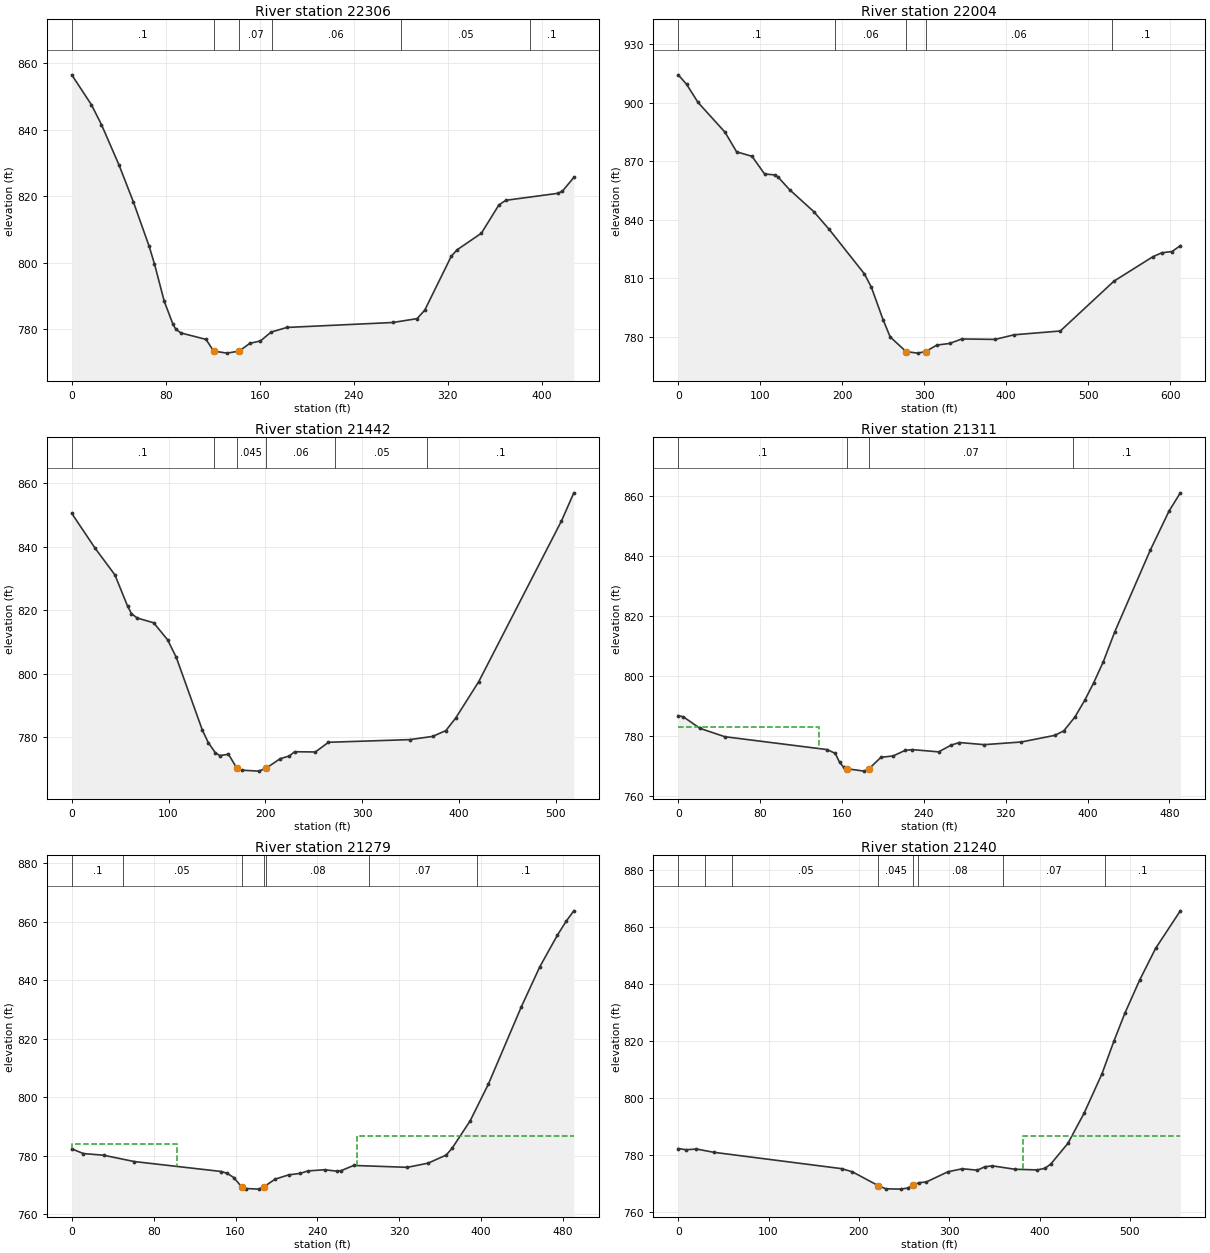
Type RM Length L Ch R = 1 ,22306   ,299.9,301.8,301.6
XS GIS Cut Line= 2
1631381.67192079372296.8071792351631760.71982774 372494.13236082
#Sta/Elev= 30
       0  856.56    16.7  847.56    25.3  841.54    40.2   829.4    52.4   818.3
    65.9  804.85    70.4  799.56    78.7  788.33      86  781.53    88.4  779.97
    92.9  778.78   114.3  776.83   120.7  773.32   132.1   772.7   142.5  773.31
   151.6  775.66   160.6  776.38   169.6  779.03   183.1  780.44   273.3  781.93
   293.9   783.1   300.4  785.64   322.9  801.83   327.8   803.8   348.6  808.83
   363.5  817.35   369.4  818.75   413.8  820.86   417.6  821.52   427.3  825.65
#Mann= 6 ,-1,0
       0      .1       0   120.7    .045       0   142.5     .07       0
     170     .06       0     280     .05       0     390      .1       0
Bank Sta=120.7,142.5
XS Rating Curve= 0 ,0
Exp/Cntr(USF)=0,0
Exp/Cntr=0.3,0.1

Type RM Length L Ch R = 1 ,22004   ,562.8,562,560.8
XS GIS Cut Line= 6
1631083.53737203372453.2623723141631163.33773738372502.454531147
 1631386.6716083372640.3974967291631450.48119196372679.809491395
1631524.92559687372725.790698646 1631604.7361328372774.989419146
#Sta/Elev= 30
       0  914.33    10.1  909.54    24.2  900.16    57.1   884.9    71.2  874.87
      90  872.56   105.3  863.53   118.2  862.99     122  861.84   135.8  855.46
   165.2  844.27     184  835.18   227.1   812.3   235.7  805.37   249.8  788.89
   258.6  779.96     278  772.45   292.1  771.67   301.8772.4769   315.6  775.81
   331.2  776.64   345.8  778.93   386.5   778.7   409.8  781.07   466.1  783.02
   531.6  808.58   578.9  821.06   589.9  823.11   602.4  823.75   612.5  826.75
#Mann= 5 ,-1,0
       0      .1       0  191.24     .06       0     278    .045       0
   301.8     .06       0  528.74      .1       0
Bank Sta=278,301.8
XS Rating Curve= 0 ,0
Exp/Cntr(USF)=0,0
Exp/Cntr=0.3,0.1

Type RM Length L Ch R = 1 ,21442   ,135.4,131,127.1
XS GIS Cut Line= 6
1630937.94205374372988.3717596591630989.80175409373058.772146146
1631145.64297784373138.3868163181631212.43221434373172.507154907
1631290.35299026373212.314489986 1631374.1963265373254.266505818
#Sta/Elev= 30
       0  850.44    23.9  839.58    44.6  831.09    57.6  821.33    61.7  818.93
    67.5  817.56    84.6  816.05      99   810.7     108  805.16     135  782.24
     141  778.41   148.4  775.17   152.9  774.31   161.9  774.73   170.5  770.35
   175.4  769.72   193.3  769.42   200.7770.3311   215.3  773.32   224.8  774.19
   230.2  775.52   251.7  775.44   265.2  778.49   349.1  779.32   372.9  780.34
   386.5  782.17   396.7  786.13   420.5  797.58   505.9  848.06   518.7   856.9
#Mann= 6 ,-1,0
       0      .1       0  147.44     .06       0   170.5    .045       0
   200.7     .06       0  272.44     .05       0  367.44      .1       0
Bank Sta=170.5,200.7
XS Rating Curve= 0 ,0
Exp/Cntr(USF)=0,0
Exp/Cntr=0.3,0.1

Type RM Length L Ch R = 1 ,21311   ,32.7,32.5,32.6
XS GIS Cut Line= 6
1630876.35644131373180.0579575721630925.73380984373224.618021857
1630962.46575472373219.1985545791630988.96092808373220.402880641
1631212.36341253373251.7153582461631329.78520355373317.953291642
#Sta/Elev= 30
       0  786.72     5.1  786.31    21.2  782.49    45.5  779.69   145.5  775.39
   153.5  774.11   157.6  771.17   161.6  769.52   164.6768.9995   181.8   768.2
   186.4768.9752     198  772.79   210.1  773.29   221.6  775.11   228.7  775.38
   254.5  774.63   266.6  776.88   274.7  777.75     299  777.04   335.3  777.93
   367.9  780.14   376.7  781.64   387.6  786.26   397.3  791.91     406  797.73
   415.2   804.6   426.6  814.75   461.1  841.86   479.5  854.97   490.6  861.11
#Mann= 4 ,-1,0
       0      .1       0   164.6    .045       0   186.4     .07       0
  385.75      .1       0
#XS Ineff= 2 , 0
          137.64  782.79
Permanent Ineff=
       F       F
Bank Sta=164.6,186.4
XS Rating Curve= 0 ,0
Exp/Cntr(USF)=0,0
Exp/Cntr=0.3,0.1

Type RM Length L Ch R = 1 ,21279   ,47.7,38.7,34.6
XS GIS Cut Line= 6
1630867.62507736373211.6715166931630917.00244589373256.231580978
1630953.73439077  373250.81211371630980.22956413373252.016439762
1631203.63204859373283.3289173671631321.05383961373349.566850763
#Sta/Elev= 30
       0   782.3    11.4   780.7    31.1  780.13      61  777.97   146.2  774.56
   151.8  773.94   158.3   772.5   165.9  769.33   170.4  768.74   182.6  768.53
   188.1769.4186   198.7  771.94     212  773.42   222.9   773.9     231  774.77
   247.2  775.16   259.3  774.66   263.3  774.87   275.5  776.63     328  775.99
   348.2  777.42   365.8  780.17   371.7  782.55   389.3  791.91   407.1  804.47
   439.2  830.84   457.3  844.58   474.4  855.34   483.2  860.24   490.6  863.74
#Mann= 7 ,-1,0
       0      .1       0      50     .05       0   165.9    .045       0
   188.1     .05       0  190.16     .08       0  290.16     .07       0
  395.75      .1       0
#XS Ineff= 2 , 0
          102.59  784.03   278.4          786.61
Permanent Ineff=
       F       F
Bank Sta=165.9,188.1
XS Rating Curve= 0 ,0
Exp/Cntr(USF)=0,0
Exp/Cntr=0.3,0.1

Type RM Length L Ch R = 1 ,21240   ,56.2,62.7,66.2
XS GIS Cut Line= 6
1630822.46285004373197.8217669831630879.66833798373267.070515534
1630944.70194531373303.8024604171631096.44702909373289.350547676
1631195.80392919373316.4478840651631316.83869839373373.653371998
#Sta/Elev= 30
       0  782.25     8.8  781.81    20.1  782.07    39.8   780.9   180.8  775.18
   192.7  774.08   221.6  769.18   229.8   768.1   246.1  767.98   254.2  768.36
   259.8  769.26   266.4  770.24   274.6  770.49   298.7  774.09   314.7  775.14
   331.2  774.63   339.5  775.84   347.8  776.16   372.6  774.97   397.5  774.73
   406.1  775.29   412.6  776.84   431.4  784.05   449.4  794.68   469.1  808.46
   482.4     820   494.5  829.78   510.9  841.44   528.6   852.6   555.9  865.76
#Mann= 8 ,-1,0
       0     .05       0      30      .1       0      60     .05       0
   221.6    .045       0   259.8     .05       0  265.46     .08       0
  359.08     .07       0  472.06      .1       0
#XS Ineff= 2 , 0
                          381.75           786.7
Permanent Ineff=
       F       F
Bank Sta=221.6,259.8
XS Rating Curve= 0 ,0
Exp/Cntr(USF)=0,0
Exp/Cntr=0.3,0.1

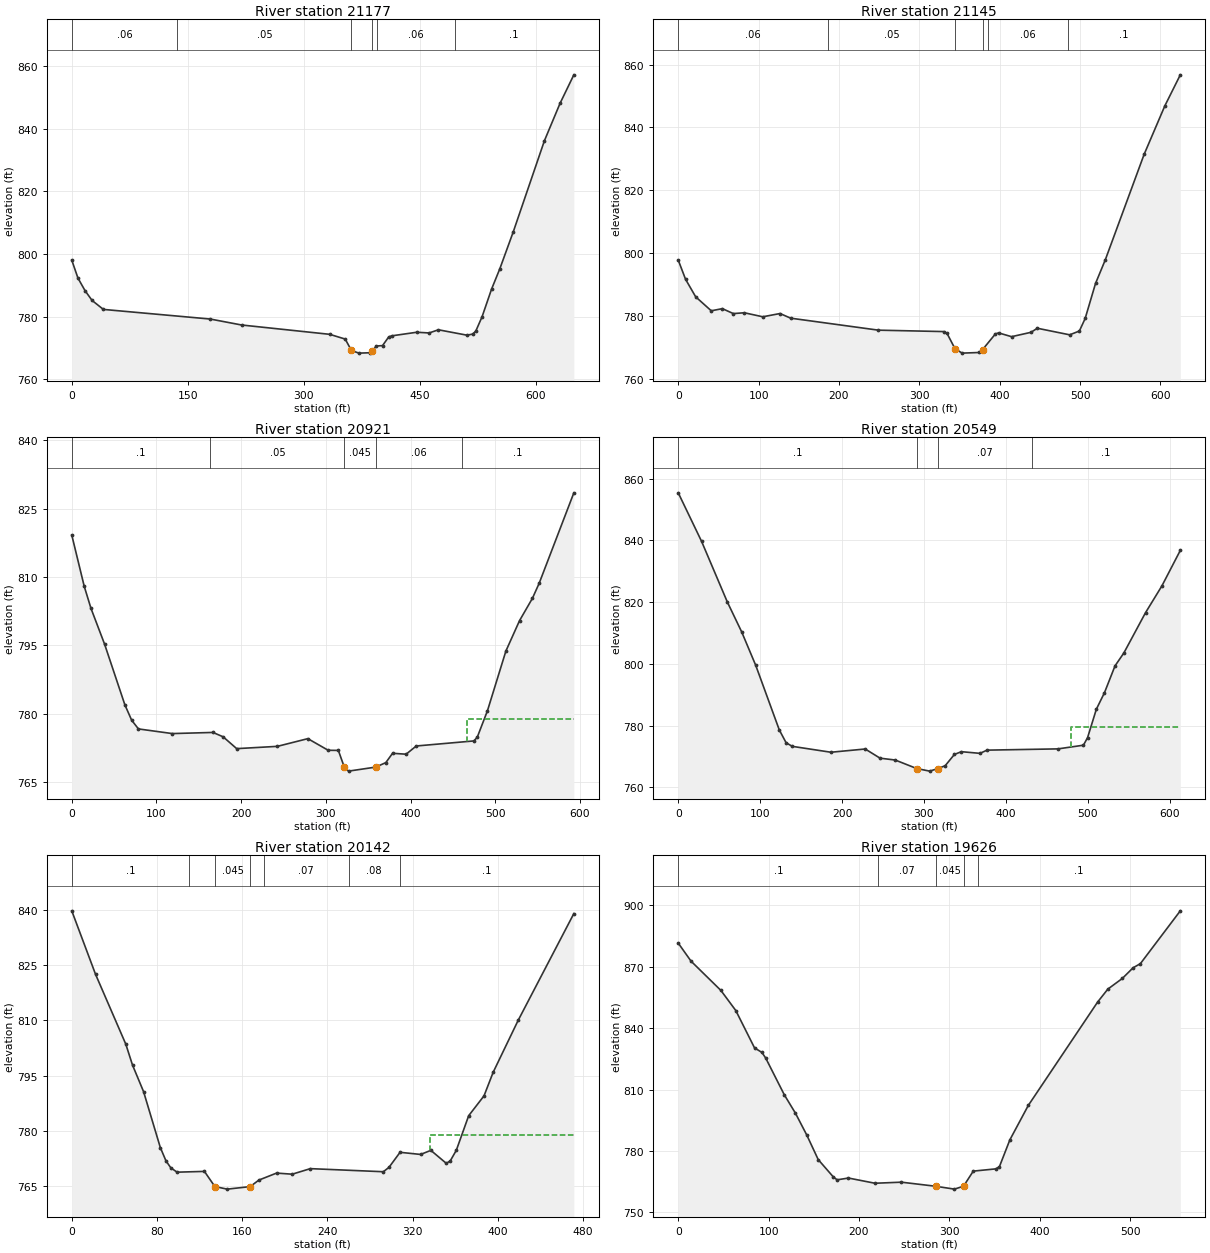
Type RM Length L Ch R = 1 ,21177   ,32.5,32.9,33.5
XS GIS Cut Line= 6
1630661.08315777373401.0517899031630771.88115545373339.631160754
1630847.75369734373331.8030413521630967.58414048373354.685236526
1631145.22223459373370.943638359  1631289.741362373390.815018378
#Sta/Elev= 30
       0  798.02       8  792.28    17.2  788.25    26.3  785.13    40.9  782.27
   179.2  779.19   219.6  777.29   333.5  774.31   353.6  772.79   361.6  769.14
   371.3   768.3   385.7  768.42   388.8769.0788   393.8  770.57   401.8   770.7
   409.8  773.47   413.9  773.83     446  774.97   462.1  774.75   474.1  775.76
   510.9  774.04   518.4  774.38   522.4  775.34   530.5   779.9   542.8  788.75
   553.5  795.27   570.9  807.09   611.2  836.22   631.4  848.16   649.2  857.25
#Mann= 6 ,-1,0
       0     .06       0  136.68     .05       0   361.6    .045       0
   388.8     .05       0  394.95     .06       0  494.95      .1       0
Bank Sta=361.6,388.8
XS Rating Curve= 0 ,0
Exp/Cntr(USF)=0,0
Exp/Cntr=0.3,0.1

Type RM Length L Ch R = 1 ,21145   ,224.9,223.4,221.8
XS GIS Cut Line= 6
1630676.13723354373435.0740011471630786.93523122373373.653371998
1630862.80777311373365.8252525971630982.63821626 373388.70744777
1631160.27631036373404.9658496041631280.70891654373420.622088406
#Sta/Elev= 30
       0  797.74     9.1  791.64    21.7  786.05    41.1   781.6    54.9  782.28
    68.6  780.71    82.3  780.97   105.2  779.69   126.7  780.73   139.9  779.25
   249.1  775.43   330.5  774.98   334.5   774.4   344.4769.5275   353.3  768.12
   374.6  768.32   378.7  769.24   394.7  774.24   398.7  774.56   414.8  773.36
   438.9  774.74   446.9  776.04   487.1  773.95   499.2  775.16   506.4  779.16
   519.3  790.31   531.4  797.79   579.8  831.43   605.6  846.88   624.8  856.73
#Mann= 6 ,-1,0
       0     .06       0  186.68     .05       0   344.4    .045       0
   378.7     .05       0  384.95     .06       0  484.95      .1       0
Bank Sta=344.4,378.7
XS Rating Curve= 0 ,0
Exp/Cntr(USF)=0,0
Exp/Cntr=0.3,0.1

Type RM Length L Ch R = 1 ,20921   ,380.6,372.5,358.6
XS GIS Cut Line= 4
1630681.41533191373614.1049314241630775.16547248373614.435967515
 1631171.8383792373614.4359675151631265.58851978373573.645232304
#Sta/Elev= 30
       0   819.2    14.7  807.97    22.7  803.12    38.7  795.31    62.7  781.99
    70.7  778.62    78.7  776.71   118.7  775.69   166.7  775.94   178.7  774.98
   194.7  772.39   242.7  772.89   278.7  774.58   302.7  772.03   314.7     772
   321.7768.3474   326.7  767.46   358.8768.3436   370.7  769.32   378.7  771.37
   394.7  771.17   406.7  772.97   474.7  774.08   478.7   774.9   490.7  780.69
   512.5  793.79   528.6  800.45   543.8  805.34   551.8  808.65   592.7  828.46
#Mann= 5 ,-1,0
       0      .1       0  163.75     .05       0   321.7    .045       0
   358.8     .06       0  461.25      .1       0
#XS Ineff= 2 , 0
                          466.92          778.94
Permanent Ineff=
       F       F
Bank Sta=321.7,358.8
XS Rating Curve= 0 ,0
Exp/Cntr(USF)=0,0
Exp/Cntr=0.3,0.1

Type RM Length L Ch R = 1 ,20549   ,407,406.3,405.4
XS GIS Cut Line= 6
1630900.83747576 374147.067292751630977.70149526 374092.87678434
1631044.44250351 374036.290939511631235.13077043 373874.61869067
1631303.06600201373819.4419637621631378.49662542373763.441091508
#Sta/Elev= 30
       0  855.41    28.5  839.68    59.9  820.06    77.4  810.38    94.6  799.52
   123.4  778.57   131.7  774.43   139.2  773.26   186.4  771.35   228.3   772.4
   246.4  769.43     265  768.82   291.2  766.07     307  765.23   316.6766.0167
   325.9  766.98   337.2  770.64   345.7  771.53   368.4  770.99     377  772.03
   463.7  772.44   494.7  773.63   499.8   776.1   510.5   785.3   520.4  790.64
   533.3  799.34   544.1  803.53   570.5  816.56   590.5  825.24     613  836.76
#Mann= 4 ,-1,0
       0      .1       0   291.2    .045       0   316.6     .07       0
  431.55      .1       0
#XS Ineff= 2 , 0
                           479.2          779.45
Permanent Ineff=
       F       F
Bank Sta=291.2,316.6
XS Rating Curve= 0 ,0
Exp/Cntr(USF)=0,0
Exp/Cntr=0.3,0.1

Type RM Length L Ch R = 1 ,20142   ,507.7,516.2,520.7
XS GIS Cut Line= 3
1631196.54981558374392.4486838971631431.86171338374194.060385702
1631567.52979338374102.939810917
#Sta/Elev= 30
       0  839.78    22.3  822.53    50.7  803.54      57  797.85    67.4  790.61
    83.1  775.43    88.4  771.81    92.9  769.93    98.8  768.73   124.5  768.94
   134.3764.8153   145.9  764.12   167.4   764.8   175.6  766.58   192.2  768.48
   206.9  768.18   223.9  769.69   292.4  768.85   297.7  770.04   308.1  774.13
   327.4  773.55     337  774.66   351.5  771.13   355.2  771.79   360.9  774.68
   372.5  784.08   386.9  789.48   395.5   795.9   418.9  809.98   471.2  839.03
#Mann= 7 ,-1,0
       0      .1       0     110     .06       0   134.3    .045       0
   167.4     .06       0     180     .07       0     260     .08       0
  307.78      .1       0
#XS Ineff= 2 , 0
                          335.79          778.91
Permanent Ineff=
       F       F
Bank Sta=134.3,167.4
XS Rating Curve= 0 ,0
Exp/Cntr(USF)=0,0
Exp/Cntr=0.3,0.1

Type RM Length L Ch R = 1 ,19626   ,503.9,504.9,505.2
XS GIS Cut Line= 4
1631314.36902886374796.5708451571631441.81559372374764.043308584
1631646.45054416374700.826392573 1631856.2649906374694.467353851
#Sta/Elev= 30
       0  881.46    14.2  872.63    47.2  858.37    63.7  848.55    84.4  830.35
    92.6   828.1    96.8  825.36   117.4  807.41   129.7  798.46   142.3  787.74
   154.9  775.82   171.6  767.36   175.8  765.94   188.4  766.81   217.7  764.27
     247  764.79   284.7  762.81   305.6   761.4   315.7762.8214   326.5  770.19
   351.4  771.28   355.4  772.34     367  785.46   387.4  802.26   464.1   852.7
   475.4  859.01   491.4   864.2   503.4  869.44   511.4  871.42   555.6  897.21
#Mann= 5 ,-1,0
       0      .1       0  221.53     .07       0   284.7    .045       0
   315.7     .07       0  331.53      .1       0
Bank Sta=284.7,315.7
XS Rating Curve= 0 ,0
Exp/Cntr(USF)=0,0
Exp/Cntr=0.3,0.1

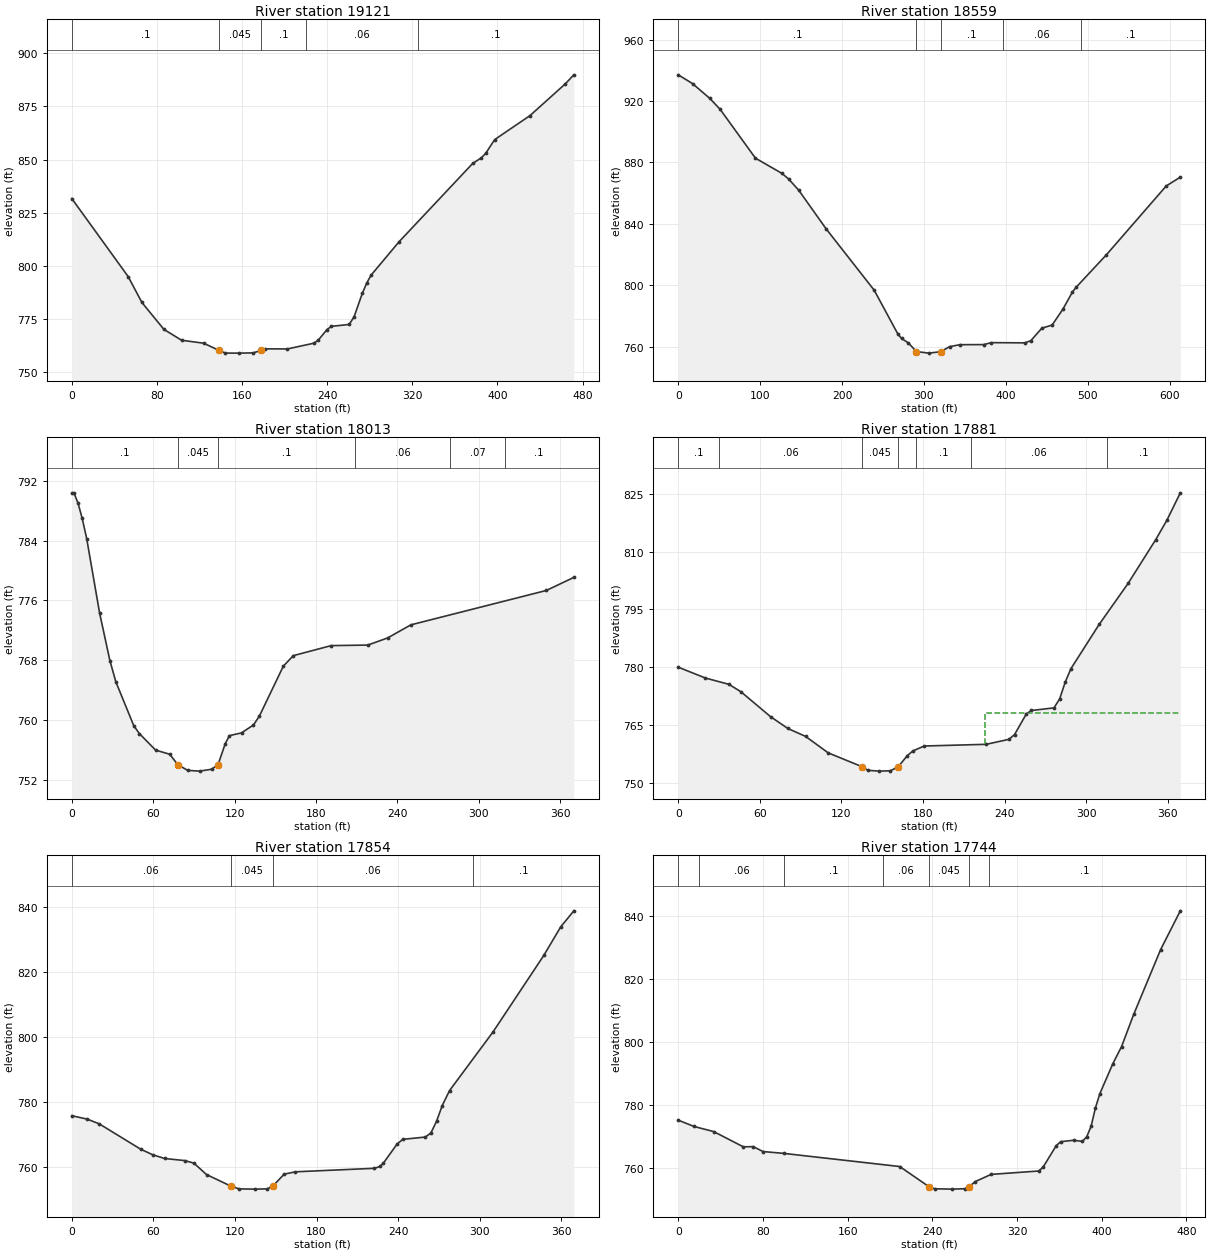
Type RM Length L Ch R = 1 ,19121   ,558.4,561.9,559.7
XS GIS Cut Line= 3
1631516.44901731375209.8110361891631763.30146953375143.482309813
1631971.87621661375086.618891343
#Sta/Elev= 30
       0  831.67      53  795.01    65.9  782.85    86.6   770.2   103.2  765.11
   123.9  763.72   138.3760.3442   144.4  759.08   157.5  759.06   170.5  759.18
   177.8  760.33   181.9  761.08   202.6  761.02   227.5  763.72   231.6  765.14
   239.9  770.15     244  771.64   260.6  772.53   265.2  775.99     273  787.11
   277.2  792.02   281.3   795.7   307.5  811.34   376.7  848.13     385  850.84
     389  852.92   397.4  859.35   430.6  870.63   463.8  885.56   471.8  889.78
#Mann= 5 ,-1,0
       0      .1       0   138.3    .045       0   177.8      .1       0
     220     .06       0  325.61      .1       0
Bank Sta=138.3,177.8
XS Rating Curve= 0 ,0
Exp/Cntr(USF)=0,0
Exp/Cntr=0.3,0.1

Type RM Length L Ch R = 1 ,18559   ,547.3,546.1,543.3
XS GIS Cut Line= 6
1631451.37246393375797.6168131681631541.00220592375770.129663423
1631791.96627092375693.1662346721631863.66986768375671.176121175
 1631948.2205516375648.4428989291632040.58716476375629.537424922
#Sta/Elev= 30
       0  937.01    17.5  931.28    38.4  921.72      51  914.66    94.3  882.71
   126.3  872.91   134.7  869.21   147.2   861.8   180.7  836.61   239.3   796.7
   268.5  767.89   272.7   765.3   281.1  762.33   290.9756.7054   306.2  755.72
   320.7756.6838   331.3  759.93   343.9  761.21   372.9  761.28   382.5  762.55
   423.3  762.41   430.5   763.8   444.1     772   456.5  773.97   469.7  784.32
   481.4  795.57     486  798.69   522.8  819.75   595.8  864.56   613.1  870.37
#Mann= 5 ,-1,0
       0      .1       0   290.9    .045       0   320.7      .1       0
  396.25     .06       0  491.25      .1       0
Bank Sta=290.9,320.7
XS Rating Curve= 0 ,0
Exp/Cntr(USF)=0,0
Exp/Cntr=0.3,0.1

Type RM Length L Ch R = 1 ,18013   ,128.7,131.8,133.4
XS GIS Cut Line= 3
 1631934.6366128376213.1661629791632115.13561611376129.545155795
1632266.06133639376048.983453753
#Sta/Elev= 30
       0  790.41     1.6  790.41     4.6  789.03     7.6  787.05      11  784.29
    20.5  774.33    28.1  767.95    32.5   765.1    45.7  759.24    49.8  758.19
    61.8  755.97    72.2  755.42    78.1 754.033    85.4  753.26    94.2  753.16
     103  753.41   107.8754.0209   113.1  756.84   116.2  757.91   125.1  758.28
   133.9  759.34   138.3  760.54   155.9  767.21   163.3  768.62   191.2  769.96
   218.2  770.03   232.9     771   249.9  772.74   349.7  777.34     370  779.09
#Mann= 6 ,-1,0
       0      .1       0    78.1    .045       0   107.8      .1       0
  208.93     .06       0  278.93     .07       0  318.93      .1       0
Bank Sta=78.1,107.8
XS Rating Curve= 0 ,0
Exp/Cntr(USF)=0,0
Exp/Cntr=0.3,0.1

Type RM Length L Ch R = 1 ,17881   ,27.6,27.2,27.1
XS GIS Cut Line= 3
1631921.94914417376280.4009583591631999.74964003376314.660673854
 1632273.5884858376238.709892372
#Sta/Elev= 30
       0  780.07      20  777.26    37.3  775.63    46.1  773.71    67.9  767.26
    80.6  764.21    93.7  762.15   110.3  757.89   135.1 754.325   139.4  753.38
   147.7  753.17     156  753.26   161.7754.2653   168.4  757.16   172.6  758.41
   180.9  759.67   226.5  760.11   243.1  761.39   247.3  762.62     256  767.99
   259.7  768.86   276.3  769.54   280.5  771.88   284.6  776.24   288.8  779.71
   309.5  791.12   330.8  801.75   351.1  813.06   359.4  818.14   369.2  825.19
#Mann= 7 ,-1,0
       0      .1       0      30     .06       0   135.1    .045       0
   161.7     .06       0  175.01      .1       0  215.01     .06       0
  315.01      .1       0
#XS Ineff= 2 , 0
                          225.85          768.33
Permanent Ineff=
       F       F
Bank Sta=135.1,161.7
XS Rating Curve= 0 ,0
Exp/Cntr(USF)=0,0
Exp/Cntr=0.3,0.1

Type RM Length L Ch R = 1 ,17854   ,109,109.7,110.3
XS GIS Cut Line= 3
1631941.70875113376303.0117174441632019.50924699376337.271432939
1632293.34809276376261.320651458
#Sta/Elev= 30
       0  775.72    11.4  774.65    20.1  773.23    50.7   765.4    59.4  763.72
    68.2  762.55    83.2   761.9    89.8  761.12    99.1   757.6   116.8754.0812
     123  753.19   134.8  753.12   143.8   753.2   147.9  754.08   156.2  757.73
   164.5  758.45   222.6  759.53   226.8  760.13   229.1   761.1   239.2  766.98
   243.4  768.44     260  769.14   264.1  770.41   268.3  774.07   272.4  778.81
   277.8  783.45   309.8  801.51   347.2   825.1   359.6  833.86   369.2  838.76
#Mann= 4 ,-1,0
       0     .06       0   116.8    .045       0   147.9     .06       0
  295.01      .1       0
Bank Sta=116.8,147.9
XS Rating Curve= 0 ,0
Exp/Cntr(USF)=0,0
Exp/Cntr=0.3,0.1

Type RM Length L Ch R = 1 ,17744   ,274.2,304.6,330.8
XS GIS Cut Line= 3
1631915.84089785376311.7598779581631999.68852022376452.261299241
1632302.21980638376382.010588599
#Sta/Elev= 30
       0  775.09    14.9  773.08    33.5  771.45    61.5   766.6    70.8  766.66
    80.1   765.1     100   764.5   209.2  760.33   236.6753.9656   242.1  753.25
   258.5  753.14   270.8  753.27   274.9  753.97   280.4  755.52   295.5  757.83
   340.6  758.91   344.7   760.2   357.1  767.01   361.2  768.24   373.5  768.69
   381.7  768.32   385.8  769.79   389.9  773.08     394  778.94   398.1  783.42
   410.4  793.01   418.7  798.49   430.3  808.85   455.6  829.36   474.2   841.7
#Mann= 7 ,-1,0
       0      .1       0      20     .06       0     100      .1       0
  193.62     .06       0   236.6    .045       0   274.9     .06       0
  293.62      .1       0
Bank Sta=236.6,274.9
XS Rating Curve= 0 ,0
Exp/Cntr(USF)=0,0
Exp/Cntr=0.3,0.1

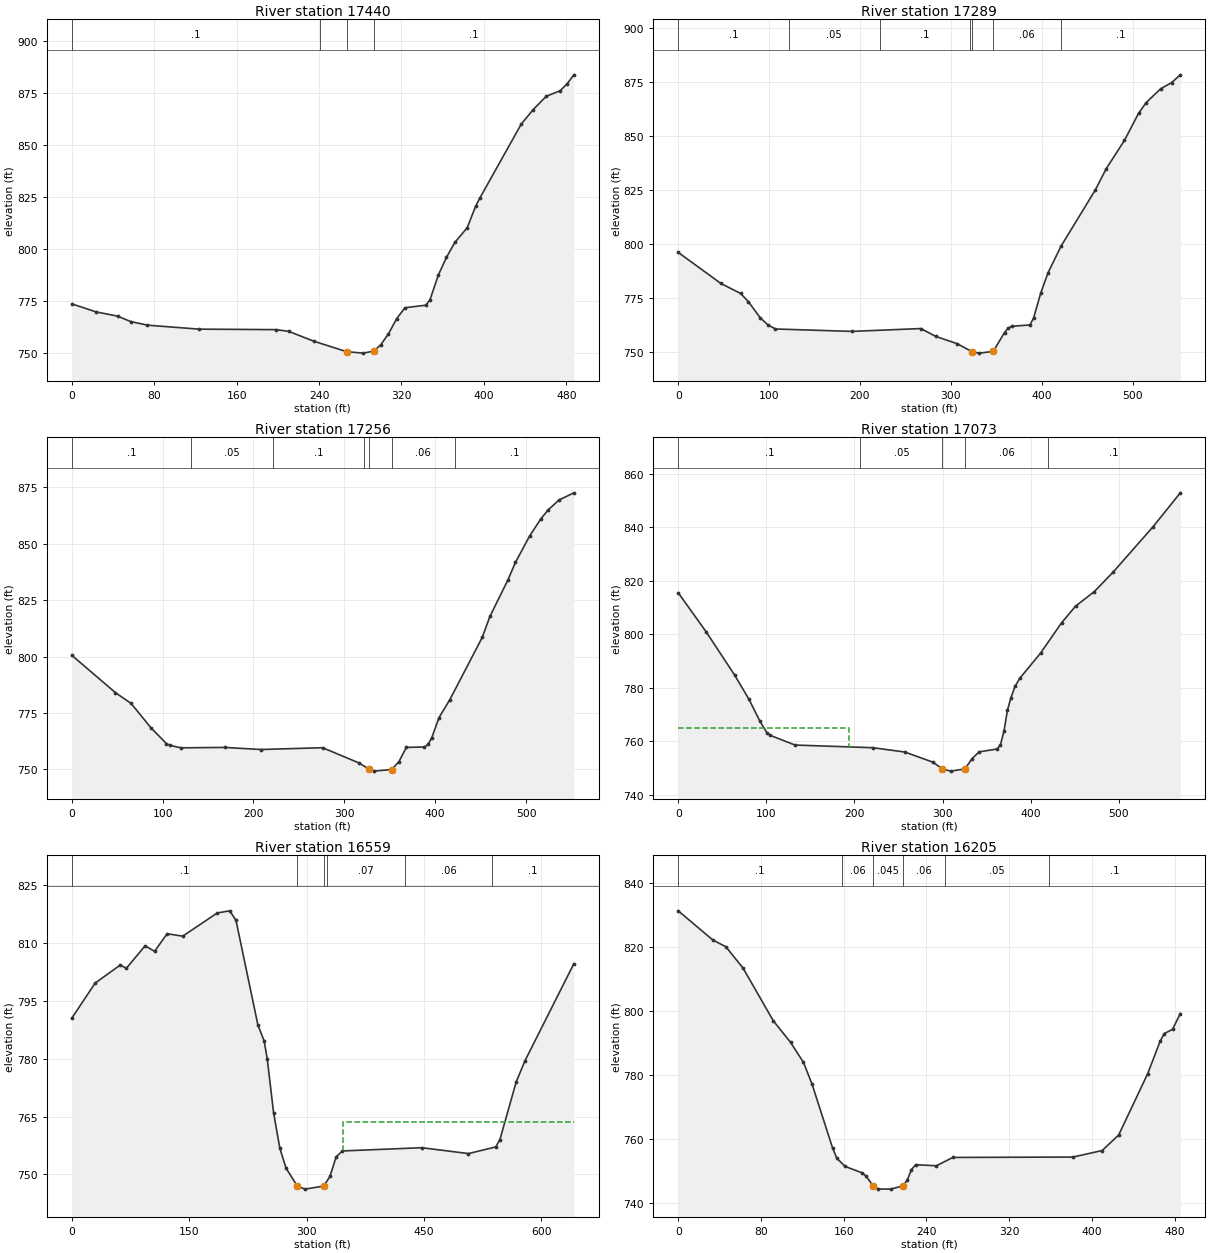
Type RM Length L Ch R = 1 ,17440   ,149.7,151.1,153.3
XS GIS Cut Line= 3
1631879.81492089376326.206893489 1631898.4850538376384.064583023
 1631952.5402826376807.135647876
#Sta/Elev= 30
       0  773.79    23.5  769.94    44.5  767.89    57.1   765.3    73.4  763.56
   123.5  761.65   198.4  761.41   210.5  760.59   234.7   755.9   266.9  750.81
   283.1  750.14   293.1751.1603   299.9  754.14   307.3  759.33   315.3  766.66
   323.4  771.92   343.5  773.14   347.6   775.6   355.6  787.41   363.7  796.14
   371.8  803.24   383.9  810.39   391.9  820.54     396   824.5   436.3  860.09
   447.8  866.99   460.5  873.38   473.9  876.04   480.7  879.32   487.3  883.69
#Mann= 4 ,-1,0
       0      .1       0   240.8     .07       0   266.9    .045       0
   293.1      .1       0
Bank Sta=266.9,293.1
XS Rating Curve= 0 ,0
Exp/Cntr(USF)=0,0
Exp/Cntr=0.3,0.1

Type RM Length L Ch R = 1 ,17289   ,32.9,32.9,32.9
XS GIS Cut Line= 3
1631740.12671702376281.0940843031631778.65130028376375.139390484
1631771.85284441376826.103629765
#Sta/Elev= 30
       0  795.98    46.9  781.58    68.6  776.95    77.2  773.14    90.2  765.67
    98.8  762.33     107  760.45     191  759.33     267  760.65   283.2  757.06
   307.1  753.61   323.1  749.98   331.1  749.25   346.7  750.05   359.1  758.79
   363.1  760.85   367.1  761.72   387.1  762.31   391.1  765.51   399.1  777.29
   407.1  786.61   421.3  798.86   459.1  824.98   471.1  834.84   491.1  847.93
   506.6  860.47   515.1  865.52   531.1  871.93   543.1  874.77   552.6  878.36
#Mann= 7 ,-1,0
       0      .1       0  121.63     .05       0  221.63      .1       0
  321.63     .06       0   323.1    .045       0   346.7     .06       0
  421.63      .1       0
Bank Sta=323.1,346.7
XS Rating Curve= 0 ,0
Exp/Cntr(USF)=0,0
Exp/Cntr=0.3,0.1

Type RM Length L Ch R = 1 ,17256   ,182,182.8,184
XS GIS Cut Line= 3
1631707.26751366376275.9952424011631745.79209691376370.040548583
1631738.99364104376821.004787864
#Sta/Elev= 30
       0  800.55    48.1  783.99    65.4  779.19      87  768.48   104.1  761.46
   108.1  760.64   120.1  759.55   168.1  759.73   208.1  758.81   276.1   759.6
   316.2  752.83   327.6749.9855   332.2  749.23   352.2  749.94   360.2  753.49
   368.2  759.73   388.2  759.93   392.2  761.07   396.2  763.99   404.2  772.93
   416.2  780.95   451.8  808.49   460.2  817.75   480.1  833.97   488.3  841.67
   503.8   853.3   516.2  860.93   524.2   864.9   536.2  869.31   552.6  872.51
#Mann= 7 ,-1,0
       0      .1       0  131.63     .05       0  221.63      .1       0
  321.63     .06       0   327.6    .045       0   352.2     .06       0
  421.63      .1       0
Bank Sta=327.6,352.2
XS Rating Curve= 0 ,0
Exp/Cntr(USF)=0,0
Exp/Cntr=0.3,0.1

Type RM Length L Ch R = 1 ,17073   ,537.7,513.7,486.7
XS GIS Cut Line= 4
1631567.94691691 376284.844270551631580.00037049376380.767307051
1631553.37152707376662.2388001081631677.74246618376806.521966606
#Sta/Elev= 30
       0  815.47    31.9  800.78      64  784.71    80.3  775.66    92.4  767.68
   100.5  763.23   104.5  762.17   132.6  758.56     221  757.56   257.2  755.95
   289.3  752.13   299.8749.6202   309.4  748.81   325.5  749.66   333.5  753.46
   341.5  756.01   361.6  757.06   365.6  758.45   369.7  763.71   373.7  771.59
   377.7  776.31   382.4  780.56   387.7  783.49   411.3  792.94   435.2  804.28
     451  810.47   472.2  815.89   493.6  823.18     539  840.17   569.9  852.83
#Mann= 5 ,-1,0
       0      .1       0  206.68     .05       0   299.8    .045       0
   325.5     .06       0  419.41      .1       0
#XS Ineff= 2 , 0
          194.26     765
Permanent Ineff=
       F       F
Bank Sta=299.8,325.5
XS Rating Curve= 0 ,0
Exp/Cntr(USF)=0,0
Exp/Cntr=0.3,0.1

Type RM Length L Ch R = 1 ,16559   ,353,354.1,355
XS GIS Cut Line= 6
1630906.33287159376808.3585580891631087.57890017376809.550812915
1631162.57710975376810.0445783441631337.57347892 376811.19582276
1631424.81772701376850.3358363361631512.50816843376924.025321499
#Sta/Elev= 30
       0  790.46    29.8  799.55    61.8  804.22    69.8   803.4    93.7  809.23
   105.8  807.79   121.8  812.34   141.8  811.72   185.8  817.72   201.8  818.28
   209.8   815.8   237.8  788.69   245.8  784.56   249.8  779.82   257.8  765.99
   265.8  756.78   273.8   751.6   288.1  746.99   297.8  746.19   321.8  746.98
   329.8  749.47   337.8  754.58   345.8  756.08   447.2  756.92   506.8   755.4
   541.6  757.12   546.9  758.99   567.7  773.93     579  779.45   641.4  804.58
#Mann= 6 ,-1,0
       0      .1       0   288.1    .045       0   321.8      .1       0
  326.25     .07       0  426.25     .06       0  536.87      .1       0
#XS Ineff= 2 , 0
                          346.13          763.48
Permanent Ineff=
       F       F
Bank Sta=288.1,321.8
XS Rating Curve= 0 ,0
Exp/Cntr(USF)=0,0
Exp/Cntr=0.3,0.1

Type RM Length L Ch R = 1 ,16205   ,500.2,498.2,493
XS GIS Cut Line= 3
1630984.01756223377121.6183972741631106.92908277377157.998670921
1631463.61731496377179.499639863
#Sta/Elev= 30
       0  831.24    33.5   822.1      46  820.02    62.7  813.32    91.9  796.87
   108.6  790.11   121.1  783.86   129.4  777.03   149.4  756.93   153.4  753.83
   161.4   751.3   177.5  749.34   181.5  748.35   188.4  745.25   193.5  744.26
   205.5  744.21   217.5  745.25   221.5  747.04   225.5  750.28   229.6  751.85
   249.6  751.51   265.6  754.12   381.8  754.24   409.9  756.28   425.9  761.14
     454  780.34     466  790.46     470  792.85     478  794.19   485.5  799.13
#Mann= 6 ,-1,0
       0      .1       0  158.18     .06       0   188.4    .045       0
   217.5     .06       0  258.18     .05       0  358.18      .1       0
Bank Sta=188.4,217.5
XS Rating Curve= 0 ,0
Exp/Cntr(USF)=0,0
Exp/Cntr=0.3,0.1