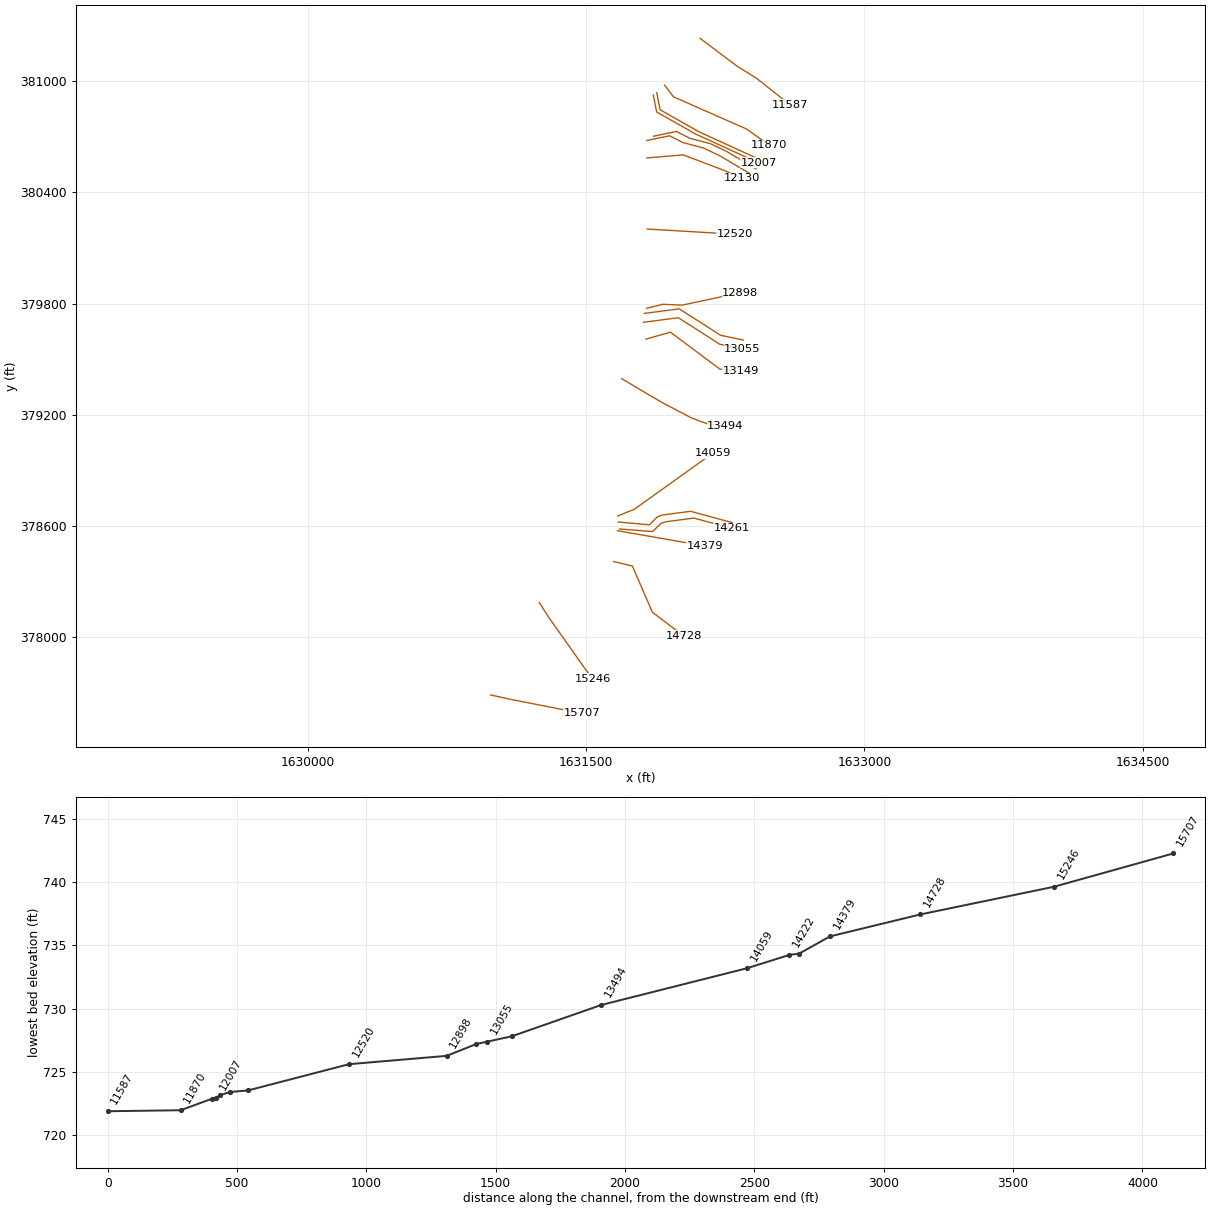
HEC-RAS study PINEYFK.prj: PINEYFK

--- PINEYFK.g01 (geometry) --- (continued)

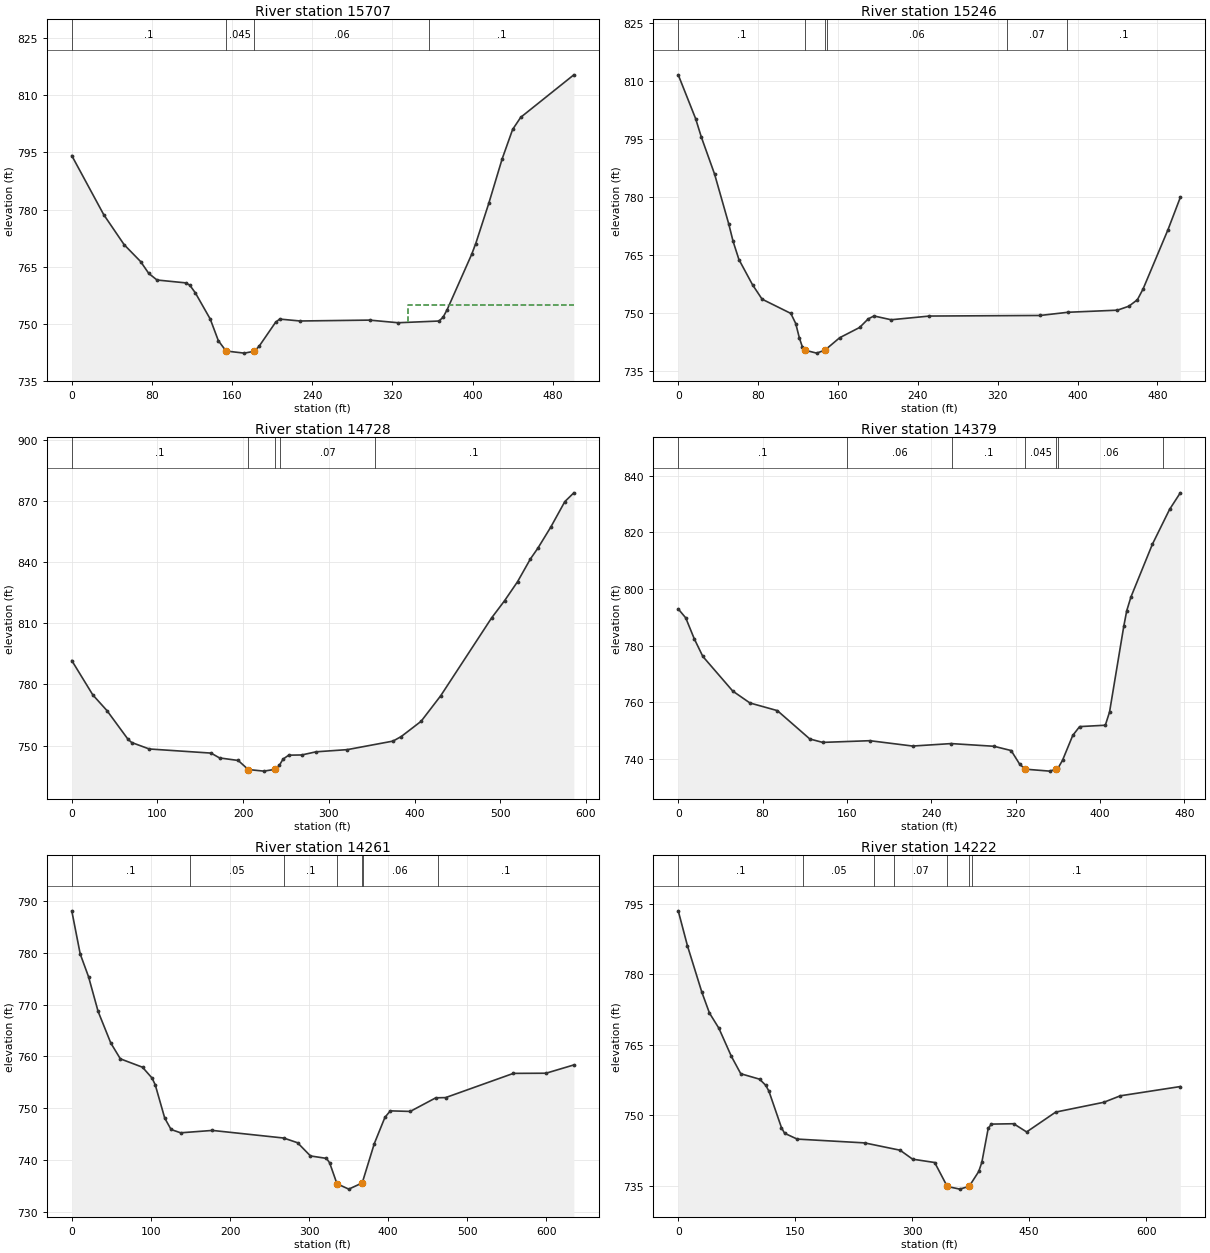
Type RM Length L Ch R = 1 ,15707   ,468.2,460.9,451.4
XS GIS Cut Line= 3
1630984.95625297377687.9012196981631098.87116238  377663.3167458
1631476.16915562377588.840604556
#Sta/Elev= 30
       0  794.17    31.9  778.66    52.3  770.77    68.7  766.35    76.9  763.21
    85.1   761.5   113.7  760.75   117.8  760.14   123.4   758.1   138.2  751.25
   146.3  745.56     154  742.85   172.2   742.3   182.3742.7971   187.1  744.15
   203.4  750.39   207.5  751.24   227.9  750.74   297.2  750.97   325.7  750.28
   366.5  750.73   370.6  751.73   374.7  753.74   399.1  768.23   403.2  771.08
   416.2  781.63   429.5  793.27     440  801.04   448.1  804.23   501.1  815.38
#Mann= 4 ,-1,0
       0      .1       0     154    .045       0   182.3     .06       0
  356.54      .1       0
#XS Ineff= 2 , 0
                          335.86          754.87
Permanent Ineff=
       F       F
Bank Sta=154,182.3
XS Rating Curve= 0 ,0
Exp/Cntr(USF)=0,0
Exp/Cntr=0.3,0.1

Type RM Length L Ch R = 1 ,15246   ,519.4,517.7,515.6
XS GIS Cut Line= 4
1631246.73414955378187.1838666741631300.29225148378103.484287047
 1631489.3611134377835.4144496281631534.27460324377774.632452905
#Sta/Elev= 30
       0  811.71    17.4  800.38    23.2  795.55    36.4  786.01    50.6  773.11
      55  768.56    60.8  763.89    74.4  757.37      84  753.63   112.8  749.94
   117.7  747.33   121.4  743.55   124.3  741.32   126.7740.4368   138.7  739.66
     147  740.44   161.7  743.64   181.7   746.3   190.3  748.52   196.1  749.28
   213.3   748.3   251.7  749.26   362.6  749.41   390.5  750.24     440  750.78
   451.5  751.81     460  753.48   465.7  756.27   490.7  771.65     503  779.98
#Mann= 6 ,-1,0
       0      .1       0   126.7    .045       0     147      .1       0
  149.37     .06       0  329.37     .07       0  389.37      .1       0
Bank Sta=126.7,147
XS Rating Curve= 0 ,0
Exp/Cntr(USF)=0,0
Exp/Cntr=0.3,0.1

Type RM Length L Ch R = 1 ,14728   ,332.8,349.1,362.7
XS GIS Cut Line= 4
1631648.14778174378407.8631637471631748.59443123378383.986221467
1631856.43409722378134.7846979121632024.43606663378007.154617378
#Sta/Elev= 30
       0  791.74    24.6  774.84    41.1  767.15    65.7  753.05    69.9   751.5
    90.4  748.33   162.5  746.31   172.4  743.94   194.2  742.69   205.9  738.24
   224.1  737.46   237.5  738.35   242.1  740.24   246.5  743.35   253.1  745.29
   268.3  745.39     285  746.94   321.5  748.01   374.8   752.2   384.4  754.43
   407.6  761.92   430.4  774.42   489.9  812.69     505  821.11   520.1  830.41
   535.1  841.59   543.8  846.86   558.9  857.24   575.3  869.75   585.8  874.04
#Mann= 5 ,-1,0
       0      .1       0   205.9    .045       0   237.5      .1       0
  243.25     .07       0  353.25      .1       0
Bank Sta=205.9,237.5
XS Rating Curve= 0 ,0
Exp/Cntr(USF)=0,0
Exp/Cntr=0.3,0.1

Type RM Length L Ch R = 1 ,14379   ,113.6,118.7,122.8
XS GIS Cut Line= 2
1631669.13619137378574.2594854691632138.15867224 378492.63726783
#Sta/Elev= 30
       0  792.95     7.1  789.81    15.2  782.42    23.3  776.21    51.7  763.97
      68  759.77      94  757.07   124.8  747.06     137  745.86   181.7  746.46
   222.3  744.57   258.8  745.44   299.4  744.49   315.7  742.98   323.8  738.15
   329.1  736.41   352.2  735.72   358.1736.3685   360.3  736.88   364.4  739.54
   374.1  748.32   380.6  751.43     405  751.92     409  756.59   422.5  786.86
   425.3  792.33   429.3  797.19   449.6  815.77   465.9  828.07   476.1  833.93
#Mann= 7 ,-1,0
       0      .1       0     160     .06       0     260      .1       0
   329.1    .045       0   358.1      .1       0     360     .06       0
     460      .1       0
Bank Sta=329.1,358.1
XS Rating Curve= 0 ,0
Exp/Cntr(USF)=0,0
Exp/Cntr=0.3,0.1

Type RM Length L Ch R = 1 ,14261   ,39.3,38.4,38.7
XS GIS Cut Line= 6
1631678.94844836378583.8239488171631857.77455337378569.923725105
1631901.67259082378613.3551743311631926.60026234378622.419782156
1632079.97271176 378642.785451841632284.56270969378587.337975477
#Sta/Elev= 30
       0  788.12    10.7  779.77    21.2  775.39    33.3  768.68    49.3  762.59
    61.4  759.53    89.4  757.91   101.5  755.81   105.5  754.51   117.5  748.08
   125.5  745.88   137.6  745.24   177.7   745.7   267.9  744.23   285.4  743.32
   301.7  740.77   321.9   740.3   325.9  739.45   335.2   735.4   350.1  734.36
   367.1  735.55   382.4  743.16   395.8  748.22   402.6  749.48   427.8  749.37
   460.1     752   472.5  752.04   558.2  756.72   599.4  756.75   634.6  758.35
#Mann= 7 ,-1,0
       0      .1       0     150     .05       0   267.9      .1       0
   335.2    .045       0   367.1      .1       0   367.9     .06       0
  462.62      .1       0
Bank Sta=335.2,367.1
XS Rating Curve= 0 ,0
Exp/Cntr(USF)=0,0
Exp/Cntr=0.3,0.1

Type RM Length L Ch R = 1 ,14222   ,156.9,162.7,170.3
XS GIS Cut Line= 6
1631672.26009632378621.4591382471631840.24726677378606.354588473
1631884.14530422378649.7860376991631909.07297574378658.850645524
1632062.44542516378679.2163152081632286.30464008378618.349371567
#Sta/Elev= 30
       0  793.53    11.8  786.09    30.2  776.24      40  771.77    52.1  768.53
    68.1  762.55    80.2  758.83   104.3  757.67   112.3  756.35   116.3  755.11
   132.4  747.34   136.4  746.15   152.5  744.91     239   744.1   284.5  742.54
   300.6  740.63   328.9  739.92     345  734.82   361.1  734.25   373.2  734.86
   385.4  738.01   389.4  739.99   397.5  747.17   401.5   748.1   430.2  748.18
   446.8  746.43   484.1  750.66   545.8  752.75     567  754.13   643.9   756.1
#Mann= 7 ,-1,0
       0      .1       0     160     .05       0  250.67      .1       0
   277.2     .07       0     345    .045       0   373.2     .07       0
   377.2      .1       0
Bank Sta=345,373.2
XS Rating Curve= 0 ,0
Exp/Cntr(USF)=0,0
Exp/Cntr=0.3,0.1

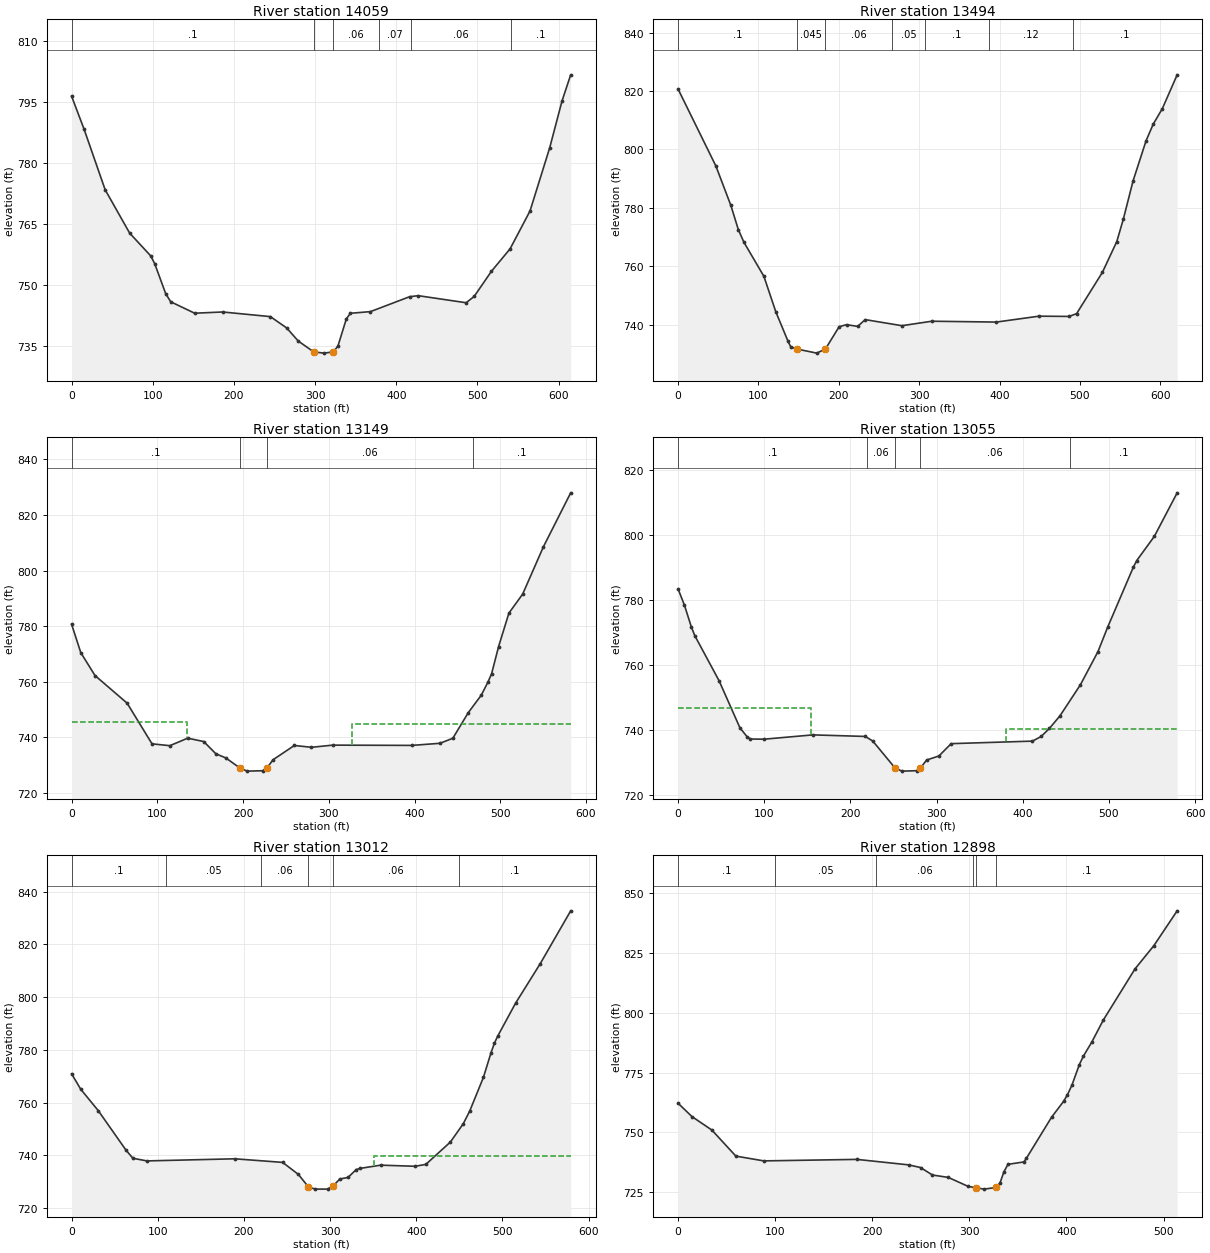
Type RM Length L Ch R = 1 ,14059   ,585.1,564.9,548.3
XS GIS Cut Line= 6
1631669.85759126378654.0464677511631758.97355476378690.041146427
1631830.12433109378740.9701784251631891.11108576378784.623634428
1631972.42653993378842.8282424211632180.79784234378991.977550417
#Sta/Elev= 30
       0  796.37    15.4  788.25    41.3  773.39    71.5  762.72    97.5  757.11
   102.4  755.19   115.9  747.83   122.1  745.83   151.6  743.02   186.1  743.32
   244.9  742.18     265  739.39   279.3  736.16   298.2733.5174   310.9   733.2
   322.3   733.5   328.1  734.93   338.5  741.64   343.5     743   368.2  743.41
   416.5  747.08   427.1  747.33   486.1  745.59     496  747.15   517.3  753.34
   540.2  758.84   564.8  768.17     589  783.68   604.2  795.21   614.9  801.65
#Mann= 6 ,-1,0
       0      .1       0   298.2    .045       0   322.3     .06       0
  378.61     .07       0  418.61     .06       0  541.11      .1       0
Bank Sta=298.2,322.3
XS Rating Curve= 0 ,0
Exp/Cntr(USF)=0,0
Exp/Cntr=0.3,0.1

Type RM Length L Ch R = 1 ,13494   ,346.6,345.1,343.3
XS GIS Cut Line= 6
1631691.75204007379394.5895323131631847.79897206 379301.81379923
 1631912.7548789379264.1632839721632067.70371599379182.822567386
1632150.49816982379152.0211198011632250.38281257379136.868591053
#Sta/Elev= 30
       0  820.65      47  794.34    65.6  780.89      75  772.52      82  768.19
   106.8  756.55   121.5   744.5   136.9  734.26   140.1  732.46   147.7  731.69
   172.6  730.28   183.4  731.72   200.4  739.32   209.6  740.02   223.5  739.43
   232.8  741.75   278.5  739.67   315.7   741.2     396  740.91   449.1  742.93
   486.6  742.84   495.9   743.8     528  757.94   545.9  768.48     554  776.11
   566.1   789.2   582.3  802.96   591.2  808.64   602.5  813.94     621  825.53
#Mann= 7 ,-1,0
       0      .1       0   147.7    .045       0   183.4     .06       0
  266.62     .05       0  306.62      .1       0  386.62     .12       0
  491.62      .1       0
Bank Sta=147.7,183.4
XS Rating Curve= 0 ,0
Exp/Cntr(USF)=0,0
Exp/Cntr=0.3,0.1

Type RM Length L Ch R = 1 ,13149   ,92.9,94.1,95.2
XS GIS Cut Line= 4
1631821.82612543379608.3683151651631954.39601486379645.759822442
1632220.66886972379446.3384502981632331.71031557379433.874614539
#Sta/Elev= 30
       0  780.65    10.7  770.44    27.3   762.2    64.7  752.28    93.8  737.62
   114.6  736.96   135.4  739.66   154.1  738.45   168.4  734.01   179.8  732.57
     197  728.77   204.9   727.8   222.7  727.94   227.8728.8432   234.8  731.86
   259.8  737.03   279.8  736.38   304.8  737.16     397  737.06   429.7  737.82
   444.7  739.63   462.7  748.84   477.9  755.14     486  760.06     490  762.92
     498  772.54   510.1  784.66   526.2  791.53   550.4  808.57   582.2  827.97
#Mann= 4 ,-1,0
       0      .1       0     197    .045       0   227.8     .06       0
  467.74      .1       0
#XS Ineff= 2 , 0
          134.59  745.47   326.5          744.91
Permanent Ineff=
       F       F
Bank Sta=197,227.8
XS Rating Curve= 0 ,0
Exp/Cntr(USF)=0,0
Exp/Cntr=0.3,0.1

Type RM Length L Ch R = 1 ,13055   ,43,43,43
XS GIS Cut Line= 4
1631808.91509282379699.0545668411631996.78988567379723.676964042
 1632219.9941387379580.809897128 1632342.0305267379555.227170988
#Sta/Elev= 30
       0  783.48     7.3  778.54    15.3  771.86    19.4  769.09    47.6   755.2
    71.8   740.7    79.9  738.03    83.9  737.27     100  737.22   156.5  738.54
   217.3  738.06     226  736.63   252.1  728.25   259.9  727.38   276.9  727.51
     281  728.23   288.4   730.8   302.7  732.04   316.9  735.84   411.3  736.62
   421.4  738.06   430.9  740.52   443.2  744.41   466.9  753.96   487.3  764.19
   498.7  771.81   528.2  790.09   532.3  792.22   552.7  799.67   579.2  813.08
#Mann= 5 ,-1,0
       0      .1       0  219.48     .06       0   252.1    .045       0
     281     .06       0  454.49      .1       0
#XS Ineff= 2 , 0
          154.24  746.94  380.59          740.42
Permanent Ineff=
       F       F
Bank Sta=252.1,281
XS Rating Curve= 0 ,0
Exp/Cntr(USF)=0,0
Exp/Cntr=0.3,0.1

Type RM Length L Ch R = 1 ,13012   ,106,114.5,122.7
XS GIS Cut Line= 4
1631813.60221965379747.087524908 1632001.4770125379771.709922108
1632224.68126553379628.8428551941632346.71765353379603.260129054
#Sta/Elev= 30
       0  770.91    10.6  765.07    30.8  757.01      63  742.03    71.1   738.9
    87.3  737.89   189.5  738.69   244.9  737.33   263.2  732.76   274.8  728.04
   282.8  727.19   297.1  727.21   302.8728.2179   311.3  731.03   320.8  731.63
   330.3  734.61   335.1  735.07   358.6  736.28   398.8  735.86   411.1  736.58
   439.6  745.06   454.5  751.98   462.1  756.86   477.9  769.57   486.6  778.77
   490.7  782.58   494.7  785.35   515.2   797.7   543.8  812.67   579.2  832.74
#Mann= 6 ,-1,0
       0      .1       0     110     .05       0  219.48     .06       0
   274.8    .045       0   302.8     .06       0  449.48      .1       0
#XS Ineff= 2 , 0
                          350.51          739.61
Permanent Ineff=
       F       F
Bank Sta=274.8,302.8
XS Rating Curve= 0 ,0
Exp/Cntr(USF)=0,0
Exp/Cntr=0.3,0.1

Type RM Length L Ch R = 1 ,12898   ,381.1,377.6,371.4
XS GIS Cut Line= 4
 1631826.3509175379774.7318758941631913.59776781379796.260319478
 1632017.8407578379791.7280155661632330.56972775379858.579498273
#Sta/Elev= 30
       0  762.18    14.2  756.62    34.8  750.96    59.5  740.06    88.3  738.06
   184.1  738.69   237.4   736.4   249.7  735.28     262  732.15   278.3  731.15
   298.8  727.38   306.4726.8593   315.2  726.25   327.7726.9642   331.5  728.79
   335.6  733.51   339.7  736.62   356.1  737.62   358.6  739.07   384.7  756.36
     397  762.94     401   765.7   405.7  769.82   413.3  778.38   417.4  781.86
     426   787.7   437.9  796.95   470.6  818.38     490  828.09     514  842.66
#Mann= 6 ,-1,0
       0      .1       0   99.86     .05       0  204.21     .06       0
  304.21      .1       0   306.4    .045       0   327.7      .1       0
Bank Sta=306.4,327.7
XS Rating Curve= 0 ,0
Exp/Cntr(USF)=0,0
Exp/Cntr=0.3,0.1

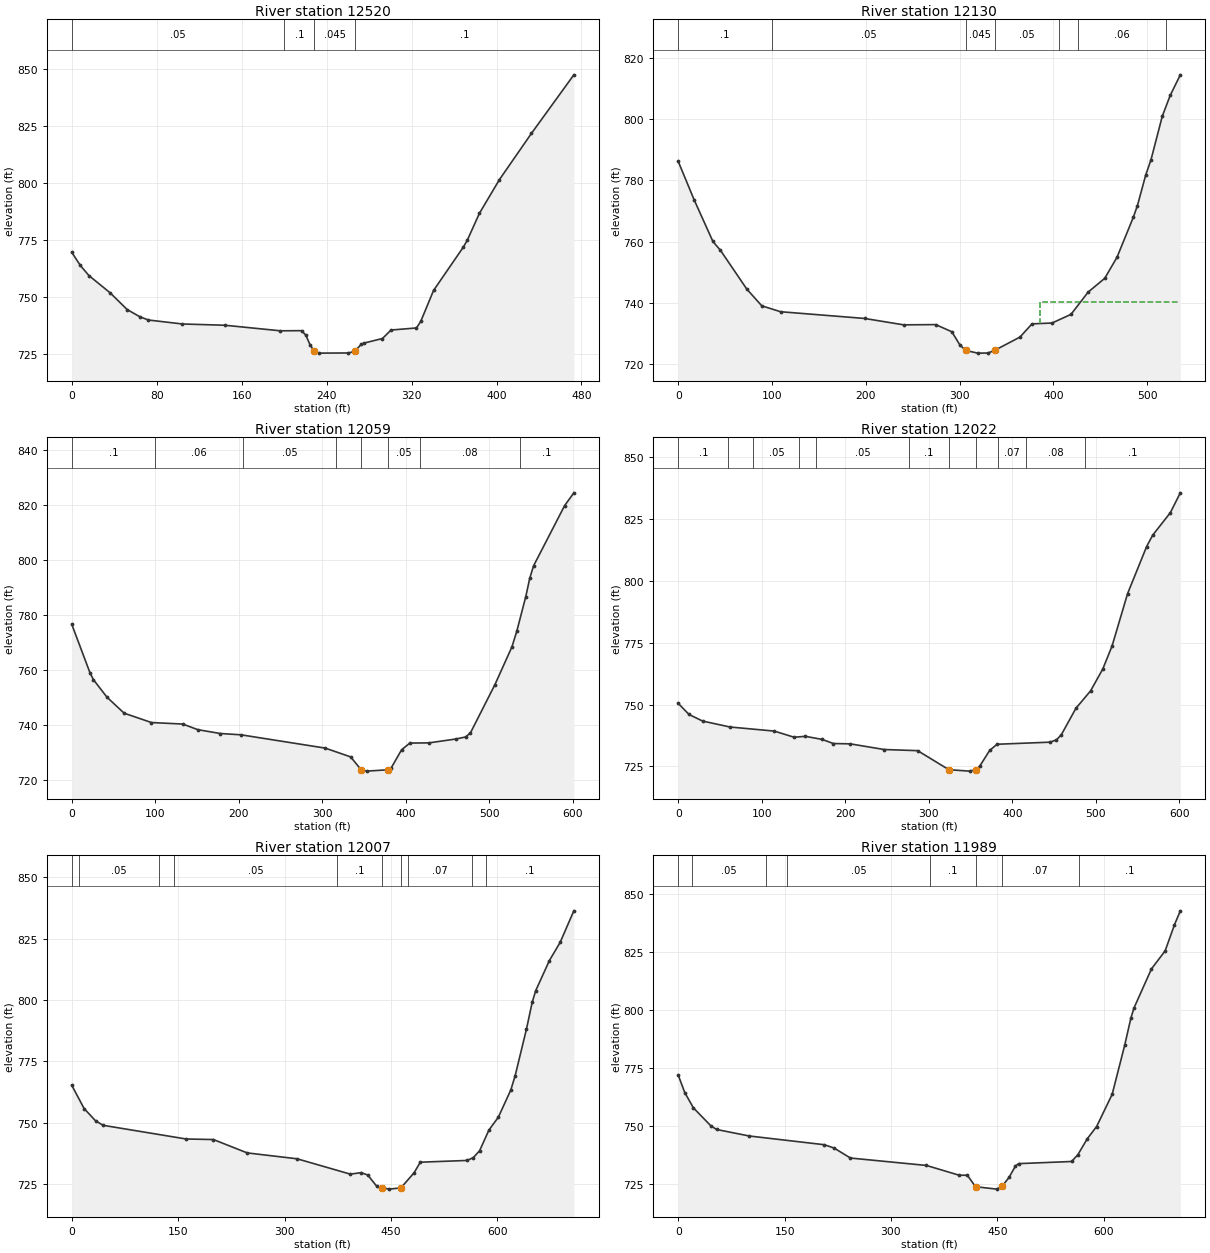
Type RM Length L Ch R = 1 ,12520   ,393,390.3,384.7
XS GIS Cut Line= 2
1631828.04927387380202.2625893581632299.99526466380174.373405812
#Sta/Elev= 30
       0   769.7     8.1  763.95    16.1  759.55    36.1  751.99    52.2  744.65
    64.2  741.48    72.2  740.08   104.2  738.34   144.3  737.79   196.4  735.36
   216.4  735.42   220.4  733.44   224.5  729.13   228.5  726.33   232.5  725.59
   260.5  725.66   266.5  726.37   272.5  729.41     275  729.96   292.6  731.99
   300.6  735.69   324.6  736.61   328.6  739.44   340.7  753.02   368.7  771.96
   372.5  775.03   383.8  786.71   402.7   801.5   432.8   821.7   472.8  847.37
#Mann= 4 ,-1,0
       0     .05       0     200      .1       0   228.5    .045       0
   266.5      .1       0
Bank Sta=228.5,266.5
XS Rating Curve= 0 ,0
Exp/Cntr(USF)=0,0
Exp/Cntr=0.3,0.1

Type RM Length L Ch R = 1 ,12130   ,71.7,70.9,69
XS GIS Cut Line= 4
1631827.27849085380586.051549293 1632023.0076051380602.464121342
1632241.58560338380519.3238211441632338.02081608380477.167514095
#Sta/Elev= 30
       0  786.21    16.9  773.69      37  760.02      45  757.15    73.1  744.47
    89.1  738.98   109.2  737.05   198.8  734.85   240.4  732.76   274.6  732.84
   291.8   730.5   300.3  726.23   306.5724.4045   319.3  723.51   330.3  723.54
   337.5724.4186   364.5  728.76   377.3  733.08   398.7  733.36   418.9  736.19
   437.2  743.47   454.9  747.98     468  754.87   485.4  767.96   489.8  771.79
   498.5  781.65   504.2  786.72   516.3  801.01   524.7  807.78   535.5  814.53
#Mann= 7 ,-1,0
       0      .1       0     100     .05       0   306.5    .045       0
   337.5     .05       0  406.42     .08       0  426.42     .06       0
  520.27      .1       0
#XS Ineff= 2 , 0
                          385.34          740.38
Permanent Ineff=
       F       F
Bank Sta=306.5,337.5
XS Rating Curve= 0 ,0
Exp/Cntr(USF)=0,0
Exp/Cntr=0.3,0.1

Type RM Length L Ch R = 1 ,12059   ,36.9,36.9,36.9
XS GIS Cut Line= 6
1631826.68257922380680.0363590111631949.14564077380705.479886439
1632021.35876944380669.1369967841632133.92646864380638.829480522
 1632218.9505583 380598.172077661632377.64679538380504.461007138
#Sta/Elev= 30
       0  776.65    21.9  758.98      26  756.54    42.2  750.19    62.7   744.4
    95.4  741.01   132.9  740.46   150.8  738.43   177.7  737.03   202.5  736.56
   303.3  731.74   333.8  728.55   346.4  723.88   352.9  723.38   378.3 723.863
   382.6  724.67   394.8  731.12   404.7  733.56   427.5  733.63   459.9  735.04
   471.4  735.78   477.2  737.25   506.5  754.75   526.9  768.48   532.7  774.13
   543.5  786.74   548.2  793.34   552.8  797.88     590  819.74     601  824.36
#Mann= 8 ,-1,0
       0      .1       0     100     .06       0  205.08     .05       0
  315.92      .1       0   346.4    .045       0   378.3     .05       0
  416.74     .08       0  536.74      .1       0
Bank Sta=346.4,378.3
XS Rating Curve= 0 ,0
Exp/Cntr(USF)=0,0
Exp/Cntr=0.3,0.1

Type RM Length L Ch R = 1 ,12022   ,15.5,14.6,14.8
XS GIS Cut Line= 6
1631863.51714171380703.2773377541631985.98020327380728.720865183
1632058.19333194380692.3779755281632170.76103114380662.070459266
1632255.78512079380621.4130564031632414.48135788380527.701985881
#Sta/Elev= 30
       0  750.51    12.9  746.02    29.2  743.36    61.9  740.96     115  739.31
   138.7  736.82   152.2  737.19   172.2  735.95   185.7  734.28   205.9  734.15
   246.5  731.86   286.6   731.4     324   723.7   348.7  723.13   356.6723.7263
   360.7  725.03   372.8   731.5   381.6  733.99     445  734.83   452.7  735.77
   458.5  737.79     476   748.5   493.6  755.57   508.2   764.4   519.3  773.69
   537.9  794.87   560.7  813.89   567.9  818.46     589  827.52     601  835.58
#Mann= 11 ,-1,0
       0      .1       0      60     .06       0      90     .05       0
  145.08     .06       0  165.08     .05       0  275.92      .1       0
     324    .045       0   356.6      .1       0   382.5     .07       0
  416.74     .08       0  486.74      .1       0
Bank Sta=324,356.6
XS Rating Curve= 0 ,0
Exp/Cntr(USF)=0,0
Exp/Cntr=0.3,0.1

Type RM Length L Ch R = 1 ,12007   ,19.9,18.6,19.1
XS GIS Cut Line= 4
1631861.45908742380925.5758852221631879.63135995380833.888510151
1632089.43850651380714.9427262751632428.92959799380559.652397325
#Sta/Elev= 30
       0  765.26    17.4  755.78    33.5   750.8      44  748.96   161.1  743.38
   199.8  743.14   247.4   737.7   317.8   735.3   392.8  729.05     408  729.65
   417.4  728.69     430  724.12   438.1   723.5   447.6  722.94   464.1723.4487
   482.7  729.59   491.5  733.92   557.5  734.63   566.3  735.81   575.1  738.59
   588.3  747.04   601.5  752.24   619.2  763.42   625.2  769.12   641.1  788.05
   649.3  799.12   654.3  803.87   673.5  816.09   688.6  823.46     708  836.36
#Mann= 10 ,-1,0
       0      .1       0      10     .05       0  123.47     .06       0
  143.47     .05       0  374.65      .1       0   438.1    .045       0
   464.1      .1       0  474.65     .07       0  564.65     .08       0
  584.65      .1       0
Bank Sta=438.1,464.1
XS Rating Curve= 0 ,0
Exp/Cntr(USF)=0,0
Exp/Cntr=0.3,0.1

Type RM Length L Ch R = 1 ,11989   ,119.1,119,118.9
XS GIS Cut Line= 4
1631880.04436615380937.5530648491631898.21663868380845.865689777
1632108.02378524380726.9199059011632447.51487672380571.629576952
#Sta/Elev= 30
       0   771.9     9.2  764.41    21.4   757.8    45.9  750.12      54  748.51
   100.3   745.7     206  741.95   219.8  740.52   242.8  736.22     350  733.03
   396.3  728.81   407.7  728.83   419.2  723.88   449.1  722.84   456.5723.9966
   466.7  727.97   475.5  732.78   479.9  733.81   554.7  734.73   563.5  737.64
   576.7  744.47     590  749.79   611.9  763.63   629.5  784.67   638.3  796.44
   642.7  800.81   667.3  817.61   686.6  825.37   699.8  836.64     708   842.6
#Mann= 8 ,-1,0
       0      .1       0      20     .05       0  123.47     .06       0
  153.47     .05       0  354.65      .1       0   419.2    .045       0
   456.5     .07       0  564.65      .1       0
Bank Sta=419.2,456.5
XS Rating Curve= 0 ,0
Exp/Cntr(USF)=0,0
Exp/Cntr=0.3,0.1

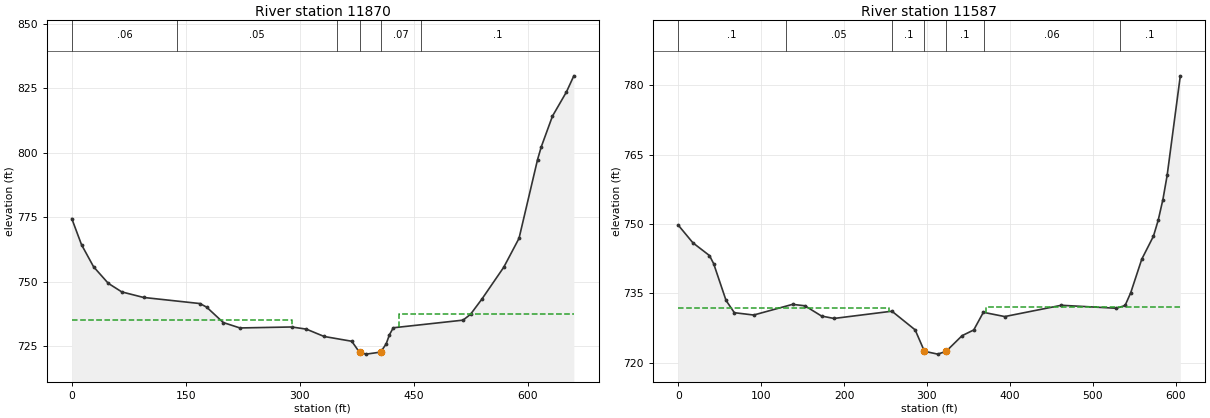
Type RM Length L Ch R = 1 ,11870   ,283.9,282.6,280.3
XS GIS Cut Line= 4
 1631922.1035375380978.7224061011631970.01225601380915.945464611
1632363.19415271380742.4828631251632487.09601092380654.925549994
#Sta/Elev= 30
       0  774.51    12.8  764.39    28.7  755.81      48   749.4    65.8  746.07
    94.4  743.92   168.7  741.55   177.5  740.14   199.3  734.18   221.2  732.09
   289.4  732.47   308.6  731.63   331.9  728.79   368.3  726.93   378.6  722.59
   387.3  721.94   406.2722.7222   413.5  725.88   417.9  729.48   422.9  732.16
   514.7  735.12   524.5  737.39   539.5  743.31   568.2  755.64   588.3  766.86
   612.7  797.42   617.6  802.38   632.3  814.25   650.7  823.64   660.4  829.87
#Mann= 6 ,-1,0
       0     .06       0  138.97     .05       0  348.97     .07       0
   378.6    .045       0   406.2     .07       0  458.97      .1       0
#XS Ineff= 2 , 0
          289.27  735.04  430.33          737.65
Permanent Ineff=
       F       F
Bank Sta=378.6,406.2
XS Rating Curve= 0 ,0
Exp/Cntr(USF)=0,0
Exp/Cntr=0.3,0.1

Type RM Length L Ch R = 1 ,11587   ,500.7,496.6,490.6
XS GIS Cut Line= 4
1632114.00950972381231.2870850651632312.42188071381081.782578803
1632417.57105283381016.1836773251632600.52870003380871.430510791
#Sta/Elev= 30
       0  749.78    17.7  745.95    37.7  743.19    42.7  741.45    57.7  733.47
    67.7  730.83      91  730.32   137.9  732.63   152.9  732.32   172.9   730.1
   187.9  729.58   257.8  731.15   285.8  727.11     297722.4763     313  721.86
   323.1722.4493   342.4  725.85   356.5  727.09   368.1  730.91   393.9  729.99
   462.1  732.43   528.6  731.79   539.1  732.39   545.9  735.16   559.2  742.41
   573.3  747.39     579  750.82   584.7  755.31   589.8  760.52   605.7  782.09
#Mann= 7 ,-1,0
       0      .1       0     130     .05       0  258.43      .1       0
     297    .045       0   323.1      .1       0  368.43     .06       0
  532.37      .1       0
#XS Ineff= 2 , 0
          253.73  731.93  370.69          732.13
Permanent Ineff=
       F       F
Bank Sta=297,323.1
XS Rating Curve= 0 ,0
Exp/Cntr(USF)=0,0
Exp/Cntr=0.3,0.1