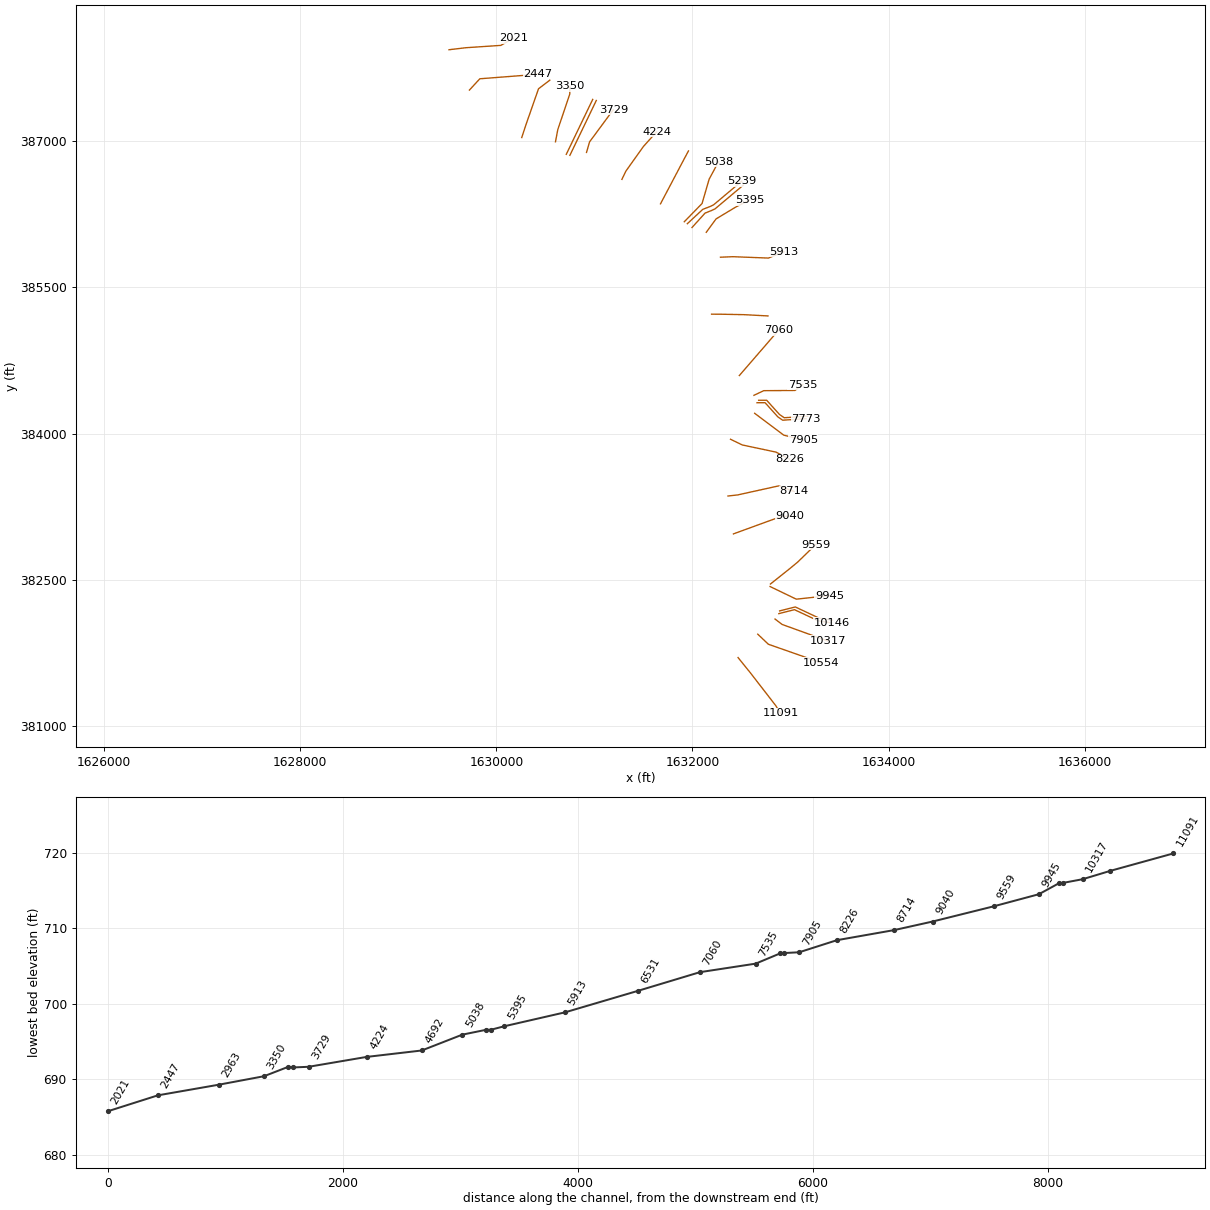
HEC-RAS study PINEYFK.prj: PINEYFK

--- PINEYFK.g01 (geometry) --- (continued)

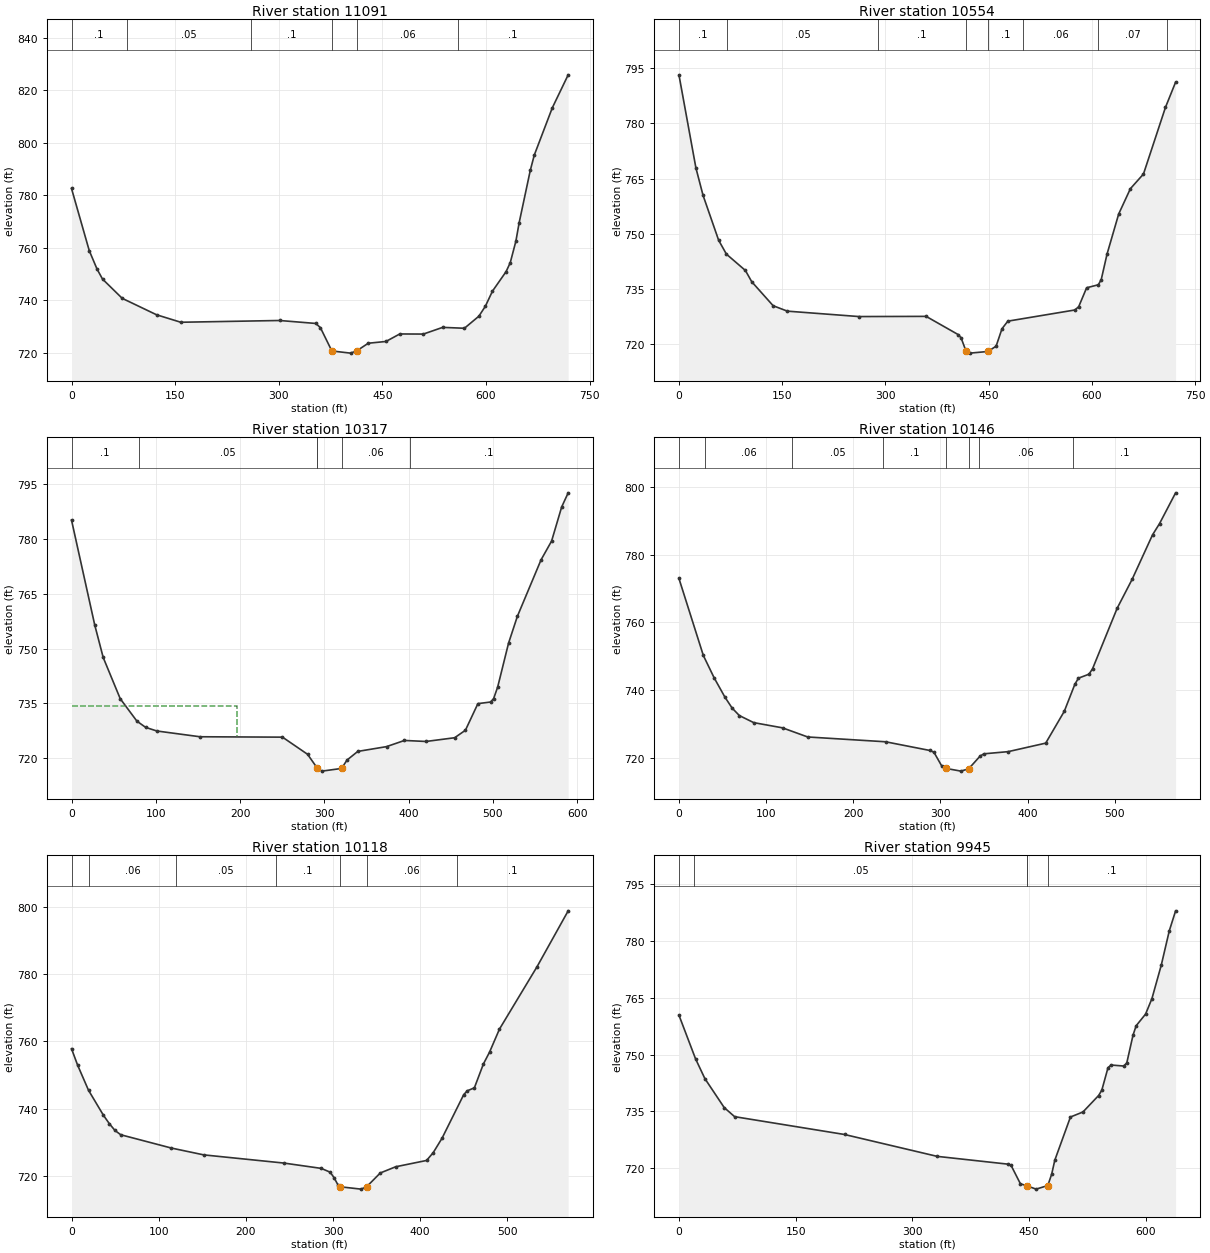
Type RM Length L Ch R = 1 ,11091   ,523.1,536.9,542.7
XS GIS Cut Line= 4
1632464.97454214381704.5522620621632590.27329067381548.780323224
1632849.58149909381212.0480570521632899.75561134381132.462258222
#Sta/Elev= 30
       0  782.63    25.7  758.95    36.9  751.96    44.9  748.12    73.4  740.78
   123.2  734.51   158.2  731.67   301.3  732.34   353.7  731.21   360.3  729.62
   376.9  720.73   403.9  719.91   412.7  720.74   429.6  723.68   455.2  724.35
   475.2  727.21   509.4  727.17   537.3  729.72   568.8  729.38   589.7  733.97
   599.1  737.76   609.4  743.52   629.1  750.95   635.1  754.33   643.3  762.56
     648  769.55   664.1  789.47   669.9  795.32     696  813.34     719  825.91
#Mann= 6 ,-1,0
       0      .1       0      80     .05       0  259.91      .1       0
   376.9    .045       0   412.7     .06       0  559.91      .1       0
Bank Sta=376.9,412.7
XS Rating Curve= 0 ,0
Exp/Cntr(USF)=0,0
Exp/Cntr=0.3,0.1

Type RM Length L Ch R = 1 ,10554   ,236.2,236.2,236
XS GIS Cut Line= 3
1632666.26112609381944.2357284131632774.23110309381841.044621721
1633314.10003501381650.896193538
#Sta/Elev= 30
       0  793.17    24.7  767.86      35  760.47    57.7  748.25      69  744.48
    96.6  740.04   105.8  736.98   136.9  730.47   157.5     729   261.6  727.53
   359.2  727.58   405.8  722.63     410  721.75     417 718.202   422.8   717.6
   449.2  718.05   460.9   719.5   469.4  724.22   477.9  726.28   575.4  729.32
   580.9  730.22   592.4  735.35   609.4  736.16   613.6  737.55   622.1  744.53
     639  755.39     656  762.26     675  766.24   706.9  784.31   721.7  791.19
#Mann= 8 ,-1,0
       0      .1       0      70     .05       0  289.35      .1       0
     417    .045       0   449.2      .1       0  499.35     .06       0
  609.35     .07       0  709.35      .1       0
Bank Sta=417,449.2
XS Rating Curve= 0 ,0
Exp/Cntr(USF)=0,0
Exp/Cntr=0.3,0.1

Type RM Length L Ch R = 1 ,10317   ,172.5,171,170
XS GIS Cut Line= 3
1632842.21566177382099.3859447261632914.73252437  382043.8652218
1633382.69290332381873.903825086
#Sta/Elev= 30
       0  785.16    27.6  756.42    37.6  747.57    57.8   736.3    77.6  730.16
      88  728.45   101.2  727.47   152.4  725.89   250.3  725.78     280   721.1
   291.7  717.26   297.1  716.49   320.3717.2242   326.9  719.53   339.6  721.88
   373.7  723.19     395  724.88   420.5   724.6   454.5  725.62   467.3  727.67
   482.1  734.95   497.1  735.39   500.8  736.35   505.6  739.52   518.4  751.44
   528.9  758.81     557  774.27   569.5   779.4   581.5  788.75   589.2   792.6
#Mann= 6 ,-1,0
       0      .1       0      80     .05       0  291.33     .06       0
   291.7    .045       0   320.3     .06       0  401.33      .1       0
#XS Ineff= 2 , 0
          196.82  734.38
Permanent Ineff=
       F       F
Bank Sta=291.7,320.3
XS Rating Curve= 0 ,0
Exp/Cntr(USF)=0,0
Exp/Cntr=0.3,0.1

Type RM Length L Ch R = 1 ,10146   ,28.9,28.8,28.8
XS GIS Cut Line= 4
1632881.02079615382154.8429735761633040.26829726382195.546537436
1633282.74833129382081.1003831431633418.28553767382059.962998544
#Sta/Elev= 30
       0  772.97      28  750.18    40.4  743.57    52.7  737.89      61  734.64
    69.3  732.42    85.8  730.33   118.8  728.79   147.7  726.09     237  724.67
     288  722.09   292.5  721.57   301.3  717.57   306.6716.7805   323.4  715.99
   332.3  716.67   345.5  720.45   349.8  721.11   377.6  721.75   420.7  724.27
     442  733.68   454.1  741.65   458.2  743.47   470.3  744.65   474.4  746.24
   502.7  764.18   519.8  772.69   543.2  785.84   551.3   789.2   569.7  798.28
#Mann= 8 ,-1,0
       0      .1       0      30     .06       0     130     .05       0
  234.37      .1       0   306.6    .045       0   332.3      .1       0
  344.37     .06       0   452.5      .1       0
Bank Sta=306.6,332.3
XS Rating Curve= 0 ,0
Exp/Cntr(USF)=0,0
Exp/Cntr=0.3,0.1

Type RM Length L Ch R = 1 ,10118   ,163.5,172.8,179.2
XS GIS Cut Line= 4
1632889.18767718382182.7578747691633048.43517829 382223.46143863
1633290.91521233382109.015284336 1633426.4524187382087.877899737
#Sta/Elev= 30
       0  757.84     7.1  752.88    19.5  745.45    36.7  737.96    43.3  735.52
    49.9  733.45    56.5  732.18   114.5  728.22   151.7  726.18   243.6  723.74
   286.5  722.15   296.7  721.02   301.1   719.4   305.6  717.25   308.4  716.66
   332.1  715.97   338.5716.6752   354.2  720.79   371.9  722.64   407.3  724.52
   414.9  726.85     425  731.14   449.9  744.15     454  745.29   462.1  746.17
   472.5  753.31   479.5  756.81   490.9  763.69   534.1  782.33   569.7  798.94
#Mann= 7 ,-1,0
       0      .1       0      20     .06       0     120     .05       0
  234.37      .1       0   308.4    .045       0   338.5     .06       0
   442.5      .1       0
Bank Sta=308.4,338.5
XS Rating Curve= 0 ,0
Exp/Cntr(USF)=0,0
Exp/Cntr=0.3,0.1

Type RM Length L Ch R = 1 ,9945    ,377.2,385.9,392.4
XS GIS Cut Line= 3
1632791.71446543 382432.573734541633058.89378106382303.063150244
 1633398.4766517382339.774811934
#Sta/Elev= 30
       0  760.39    21.3   748.9    33.3  743.67    58.2  736.01    71.6  733.61
   212.9  728.91     332  723.14   422.9  721.09   426.9  720.79     439   715.9
     447  715.41   459.1   714.5   474.2715.4412   479.2  718.47   483.2  722.14
   503.3  733.52   519.4  734.85   539.5  739.19   543.6  740.58   551.6  746.54
   555.6  747.23   571.7  746.97   575.7  747.77   583.8  755.15   587.8   757.6
   599.9  760.67     608  764.72     620  773.53   630.4  782.66   638.5   787.9
#Mann= 5 ,-1,0
       0      .1       0      20     .05       0  446.91      .1       0
     447    .045       0   474.2      .1       0
Bank Sta=447,474.2
XS Rating Curve= 0 ,0
Exp/Cntr(USF)=0,0
Exp/Cntr=0.3,0.1

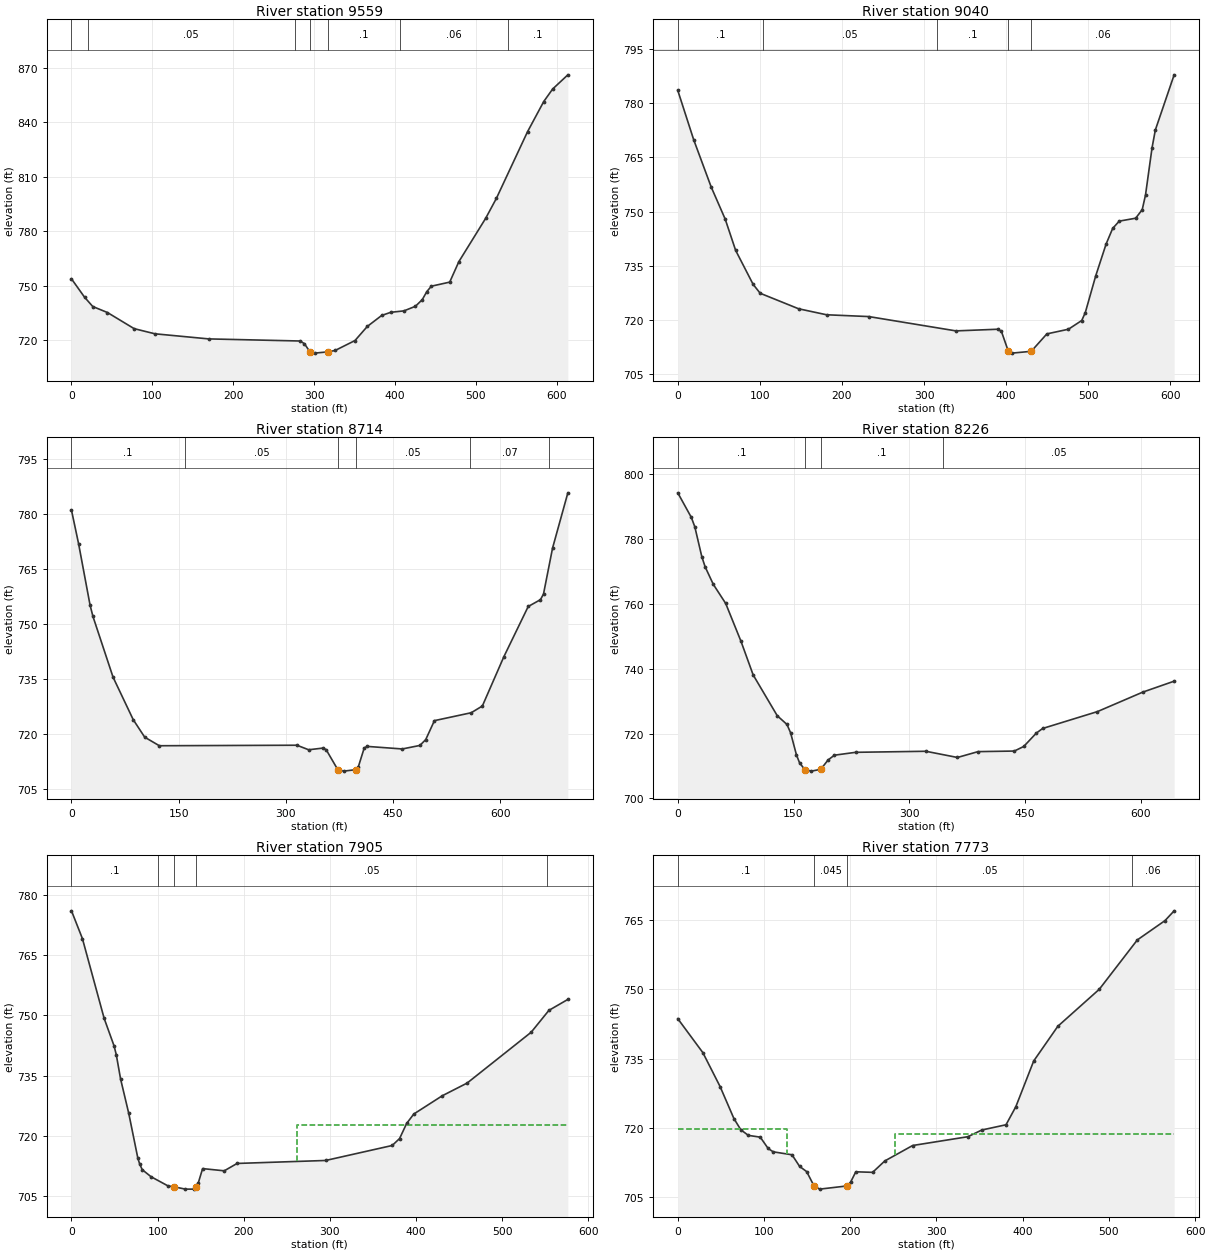
Type RM Length L Ch R = 1 ,9559    ,523,518.8,514.8
XS GIS Cut Line= 6
1632795.56006426382458.5014572591632995.65710501382618.580533415
1633072.48962851382682.6181350051633126.53545217382735.119014248
1633189.51465693382796.5503218321633257.73991418382861.565283671
#Sta/Elev= 30
       0  753.78    16.1  743.72    26.3  738.55    44.5  735.24    77.5  726.36
   103.2  723.53   169.7  720.72   282.9  719.56   288.1  718.05   294.9  713.57
   300.6  712.89   317.6  713.61   326.1  714.37   350.6  719.83   365.8  727.58
   383.6  733.63   394.8  735.36   411.1  736.15   425.3  738.67   433.8  742.35
   439.4  746.76     445  749.74   467.7  751.98     479  763.24   512.1  787.06
   525.4  798.07   563.9  834.75     584  851.41     595  858.29   613.8   866.1
#Mann= 7 ,-1,0
       0      .1       0      20     .05       0  276.25      .1       0
   294.9    .045       0   317.6      .1       0  406.27     .06       0
   539.6      .1       0
Bank Sta=294.9,317.6
XS Rating Curve= 0 ,0
Exp/Cntr(USF)=0,0
Exp/Cntr=0.3,0.1

Type RM Length L Ch R = 1 ,9040    ,328,325.8,324.2
XS GIS Cut Line= 6
1632417.88237913382972.1607958091632588.07987338383034.486458571
1632752.40828488383094.6625193221632822.83465321383120.452165903
1632904.99918705383150.5397041451632990.99293878383154.223001672
#Sta/Elev= 30
       0  783.55    19.4   769.9    40.7  756.84    57.8  747.94    70.5  739.31
    91.8  729.91   100.4  727.44   147.2  723.15   181.3  721.49   232.8  720.99
   338.9  717.03     390  717.49   394.3  716.92   402.8  711.37   407.1  710.88
   430.7711.3793   449.7   716.2     476  717.49   492.2   719.9   496.5  722.06
   509.3   732.3   521.9  741.06   529.9  745.38   537.9  747.39   557.9   748.2
   565.9  750.56   569.9  754.61   577.9  767.71   581.9  772.61   604.8  787.86
#Mann= 5 ,-1,0
       0      .1       0  103.75     .05       0  316.25      .1       0
   402.8    .045       0   430.7     .06       0
Bank Sta=402.8,430.7
XS Rating Curve= 0 ,0
Exp/Cntr(USF)=0,0
Exp/Cntr=0.3,0.1

Type RM Length L Ch R = 1 ,8714    ,490.7,488.2,483
XS GIS Cut Line= 4
1632362.27111173383360.5129663661632460.48388213383371.379163055
1632879.81261923383464.3542008721633036.15185923383406.896244177
#Sta/Elev= 30
       0  781.07     9.9  771.95      26  755.13      30  752.06    58.2  735.43
    86.4  723.83   102.5  719.03     123  716.69   315.6  716.83     332  715.59
   352.5  716.06   356.6  715.59   372.9  710.12   381.1  709.75   397.9  710.14
   401.6  710.94   409.8  716.07   413.9  716.51   463.1  715.81   487.7  716.77
   495.9  718.36   508.1  723.55   559.6  725.71   575.2  727.55   605.4  741.06
   639.4  754.75   656.5  756.61   660.8  758.16   673.5  770.73   694.9  785.82
#Mann= 6 ,-1,0
       0      .1       0  158.81     .05       0   372.9    .045       0
   397.9     .05       0  558.32     .07       0  668.32     .06       0
Bank Sta=372.9,397.9
XS Rating Curve= 0 ,0
Exp/Cntr(USF)=0,0
Exp/Cntr=0.3,0.1

Type RM Length L Ch R = 1 ,8226    ,324.7,321,315.9
XS GIS Cut Line= 4
1632388.26892047383942.2436524221632508.22808745383883.773481123
1632851.89176545383810.4375281841632992.15622575383736.998393543
#Sta/Elev= 30
       0   794.2    17.6  786.61    22.1  783.71    31.1  774.56    35.4  771.42
      46     766    62.1   760.1    81.9  748.44    97.7  738.06   128.9  725.49
   141.5   722.8   146.2  720.23   153.8   713.4   157.9  710.93   164.7708.8824
   173.2  708.41   185.3708.9733   194.7  711.83   202.9  713.32   230.5  714.21
   321.5  714.53   362.4  712.62   389.1  714.42   436.1   714.6   448.3  716.01
   464.6  720.13   472.8  721.56   543.8  726.76   602.5  732.76   643.2  736.14
#Mann= 4 ,-1,0
       0      .1       0   164.7    .045       0   185.3      .1       0
  343.45     .05       0
Bank Sta=164.7,185.3
XS Rating Curve= 0 ,0
Exp/Cntr(USF)=0,0
Exp/Cntr=0.3,0.1

Type RM Length L Ch R = 1 ,7905    ,138.7,132.7,129.7
XS GIS Cut Line= 3
1632634.61914645 384208.174042921632931.15759375383984.324685765
1633129.40056688383933.937930095
#Sta/Elev= 30
       0  775.95    12.7  769.04    37.9  749.24    49.4  742.41      52   740.2
      57  734.16    66.5   725.6      77  714.52    79.1  713.09    82.1  711.64
    92.3   709.9   112.1   707.6   118.9  707.39   132.2  706.81   142.2  706.81
   144.6707.3784   147.2  708.38   152.2  711.91   177.3  711.36   192.2  713.19
     295  713.93   372.2  717.65   380.8  719.38     389  723.13   397.3  725.47
   430.3     730   459.2  733.16   533.5  745.78   554.1  751.22   576.1  753.94
#Mann= 5 ,-1,0
       0      .1       0     100     .05       0   118.9    .045       0
   144.6     .05       0  551.54     .06       0
#XS Ineff= 2 , 0
                          262.21          722.65
Permanent Ineff=
       F       F
Bank Sta=118.9,144.6
XS Rating Curve= 0 ,0
Exp/Cntr(USF)=0,0
Exp/Cntr=0.3,0.1

Type RM Length L Ch R = 1 ,7773    ,29.3,29.4,30.3
XS GIS Cut Line= 5
1632658.98651189384316.7946719461632740.76173831384316.794671946
1632871.27169562384171.4164916531632920.00642651384137.549983744
1633158.72400665384153.244219117
#Sta/Elev= 30
       0  743.67    29.1   736.3    49.1  728.94    65.1  722.01    73.1  719.58
    81.8  718.36    95.7  717.97   104.8  715.52   110.7  714.79   132.5  714.15
   141.3  711.63   149.5   710.5     158   707.4   164.6   706.7   196.2  707.39
   200.4   708.2   206.5  710.46     226  710.34   240.1  712.81   272.4  716.16
   336.5  718.07   352.6  719.52   380.7  720.66   392.1  724.58   412.8  734.49
   440.8  742.02   488.9  750.05     533  760.75   565.1  764.94   575.7  767.06
#Mann= 4 ,-1,0
       0      .1       0     158    .045       0   196.2     .05       0
  526.49     .06       0
#XS Ineff= 2 , 0
           126.2  719.83  251.62          718.56
Permanent Ineff=
       F       F
Bank Sta=158,196.2
XS Rating Curve= 0 ,0
Exp/Cntr(USF)=0,0
Exp/Cntr=0.3,0.1

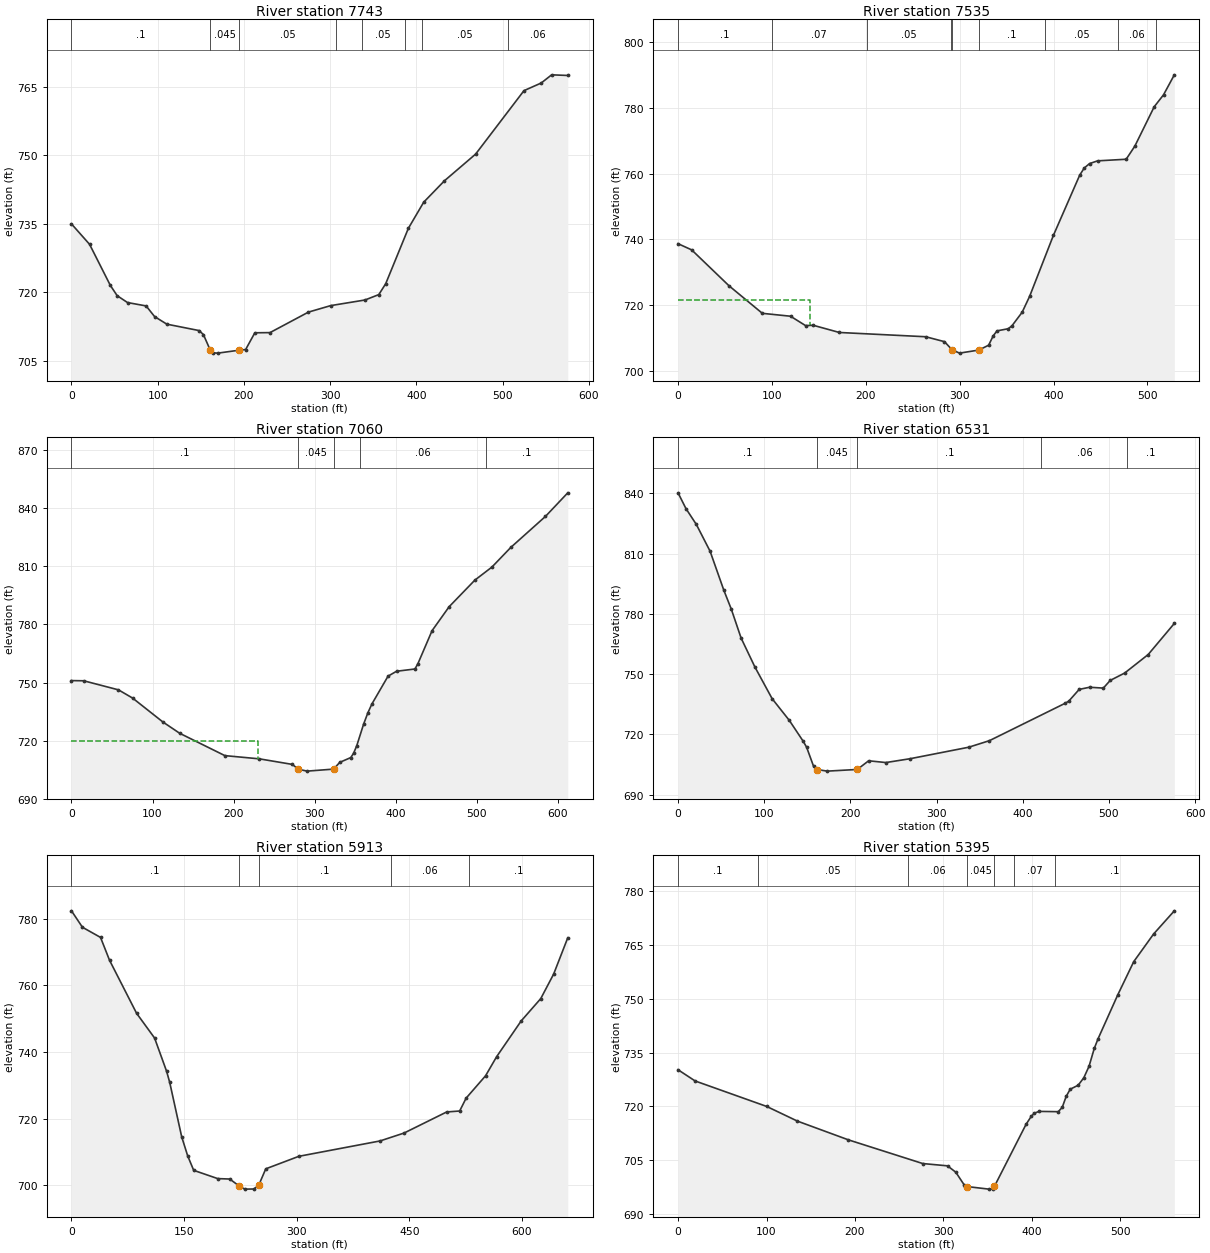
Type RM Length L Ch R = 1 ,7743    ,190.7,208.6,216.7
XS GIS Cut Line= 5
1632675.09375346384341.9880497811632756.86897988384341.988049781
1632887.37893718384196.6098694881632936.11366808384162.743361579
1633174.83124822384178.437596951
#Sta/Elev= 30
       0  734.94      21  730.47      45  721.51      53  719.23      65  717.73
    86.6  716.99    96.4  714.66   110.6     713   148.2  711.59   153.1   710.7
   160.8707.3915   164.4  706.72   169.7  706.66   194.9707.3123     202  707.44
   212.7  711.11   230.3  711.15   274.9  715.64   300.7  717.06   340.5  718.29
   356.5  719.47   364.5  721.85   390.8  733.98   408.6   739.7   432.7  744.39
   468.8  750.22   524.9  764.11   544.9  765.78     557  767.57   575.7  767.43
#Mann= 8 ,-1,0
       0      .1       0   160.8    .045       0   194.9     .05       0
  307.14      .1       0  336.49     .05       0  386.49      .1       0
  406.49     .05       0  506.49     .06       0
Bank Sta=160.8,194.9
XS Rating Curve= 0 ,0
Exp/Cntr(USF)=0,0
Exp/Cntr=0.3,0.1

Type RM Length L Ch R = 1 ,7535    ,456.1,474.5,484.7
XS GIS Cut Line= 4
1632627.05702336384392.5180231051632727.08416218384440.204927069
1633044.97855657384442.2480294831633125.34366123384501.507403968
#Sta/Elev= 30
       0  738.63    14.5  736.75    54.3  725.81    89.8  717.42   119.8  716.54
   135.8  713.69     144  713.78   171.8  711.59   263.8  710.29   283.8  708.79
   291.8  706.34   299.8   705.3   320.4 706.236   330.8  707.71   335.8  710.62
   339.8  712.08   351.8  712.74   355.8  713.68   366.5  717.74   374.5  722.61
   399.8  741.16   427.8  759.49   432.6  761.66   438.3  763.03   446.9  763.86
   477.3  764.35   486.5  768.32   507.2  780.35   517.1  783.97   528.6  790.06
#Mann= 9 ,-1,0
       0      .1       0     100     .07       0  200.81     .05       0
  290.81      .1       0   291.8    .045       0   320.4      .1       0
  390.81     .05       0  468.71     .06       0  508.71     .05       0
#XS Ineff= 2 , 0
          140.96  721.47
Permanent Ineff=
       F       F
Bank Sta=291.8,320.4
XS Rating Curve= 0 ,0
Exp/Cntr(USF)=0,0
Exp/Cntr=0.3,0.1

Type RM Length L Ch R = 1 ,7060    ,546.4,528.6,505.8
XS GIS Cut Line= 6
 1632478.2270375384595.4151624291632539.50217742 384666.36449559
1632596.59786376384732.6688249261632710.79120493384865.277155504
1632816.82741018 384988.413720251632878.10681517385059.368302763
#Sta/Elev= 30
       0  750.99    15.1  750.89      58   746.2    75.5  741.93   112.7  729.62
   133.6  723.73   189.3  712.19   231.9  710.52   272.5  707.65   280.1  705.14
   290.8  704.17   323.5 705.214   331.1  708.71   344.7  711.18   348.2  713.43
   352.1  717.35   360.5  728.43   365.8  734.34   370.8  738.92   390.7  753.28
   401.2  755.82   423.9  756.99   427.6  759.79     445  776.79   466.1   789.2
   497.8  802.93   518.9   809.7   542.1  819.82     585  835.91   612.5  848.09
#Mann= 5 ,-1,0
       0      .1       0   280.1    .045       0   323.5      .1       0
  356.25     .06       0  511.25      .1       0
#XS Ineff= 2 , 0
          229.83  719.76
Permanent Ineff=
       F       F
Bank Sta=280.1,323.5
XS Rating Curve= 0 ,0
Exp/Cntr(USF)=0,0
Exp/Cntr=0.3,0.1

Type RM Length L Ch R = 1 ,6531    ,619,618.8,612.6
XS GIS Cut Line= 4
1632194.89554596385224.2658882021632288.58393495385223.779259981
1632526.38218159385219.2566844851632770.45022682385206.200875204
#Sta/Elev= 30
       0  840.25     9.2  832.39    21.2  824.54    37.2  811.17    53.2  791.68
    61.8  782.35    73.2  767.93    89.2  753.53   109.2  737.75   129.2  726.91
   145.2  716.58   149.2   713.6   157.2  704.19   161.2  702.49   173.2  701.69
     208702.5216   221.2  706.84   241.2  705.96   269.3  707.87   337.3  713.59
   361.3  716.85   449.4  735.51   453.4  736.53   465.5  742.38   477.5  743.45
   493.5  743.03   501.5  746.85   518.3  750.53   545.6  759.75   575.9  775.23
#Mann= 5 ,-1,0
       0      .1       0   161.2    .045       0     208      .1       0
  421.53     .06       0  521.53      .1       0
Bank Sta=161.2,208
XS Rating Curve= 0 ,0
Exp/Cntr(USF)=0,0
Exp/Cntr=0.3,0.1

Type RM Length L Ch R = 1 ,5913    ,507.5,518,524.6
XS GIS Cut Line= 4
1632285.48091885 385808.040878051632411.34387822385813.412195128
1632774.39902127385799.4645804381632933.53967947385864.305140248
#Sta/Elev= 30
       0  782.38    14.6  777.45    38.7   774.4    50.7  767.54    86.7  751.64
   110.7   744.2   126.7  734.22   130.8  730.94   146.8  714.56   154.8  708.83
   162.8  704.49   194.8  702.01   210.8  701.88   222.8  699.89   230.8  698.85
   242.8  698.89   249.3699.9537   258.8  704.94   302.9   708.7     411  713.31
     443  715.68   499.8  722.01   517.1   722.3   525.7  726.16   551.6  732.87
   566.3  738.59   599.1  749.35   625.1  756.03   642.3   763.4   661.1  774.29
#Mann= 5 ,-1,0
       0      .1       0   222.8    .045       0   249.3      .1       0
  425.98     .06       0   529.3      .1       0
Bank Sta=222.8,249.3
XS Rating Curve= 0 ,0
Exp/Cntr(USF)=0,0
Exp/Cntr=0.3,0.1

Type RM Length L Ch R = 1 ,5395    ,110.2,113.4,115.8
XS GIS Cut Line= 4
1632140.71160087386063.509253703 1632240.9901278386200.913199678
1632443.12081573386323.0423730831632580.93967091386393.437662797
#Sta/Elev= 30
       0  730.22    19.3   727.1   100.3     720     135  715.92   192.6  710.71
   276.6  704.12   304.6  703.48     314   701.7   323.3  698.23   326.5  697.72
   351.3     697   355.6   697.1   357.6  697.75   393.4  715.03   399.3  717.26
   402.8  718.14   408.1  718.63   429.8  718.55   434.3  719.76   438.8  722.83
   443.3   724.8   452.3  725.91   458.7  727.99   464.6  731.19   470.5  736.15
   474.8  738.85   497.2  751.13   515.1  760.29   537.6     768     561  774.44
#Mann= 7 ,-1,0
       0      .1       0      90     .05       0   260.1     .06       0
   326.5    .045       0   357.6     .06       0   380.1     .07       0
  426.27      .1       0
Bank Sta=326.5,357.6
XS Rating Curve= 0 ,0
Exp/Cntr(USF)=0,0
Exp/Cntr=0.3,0.1

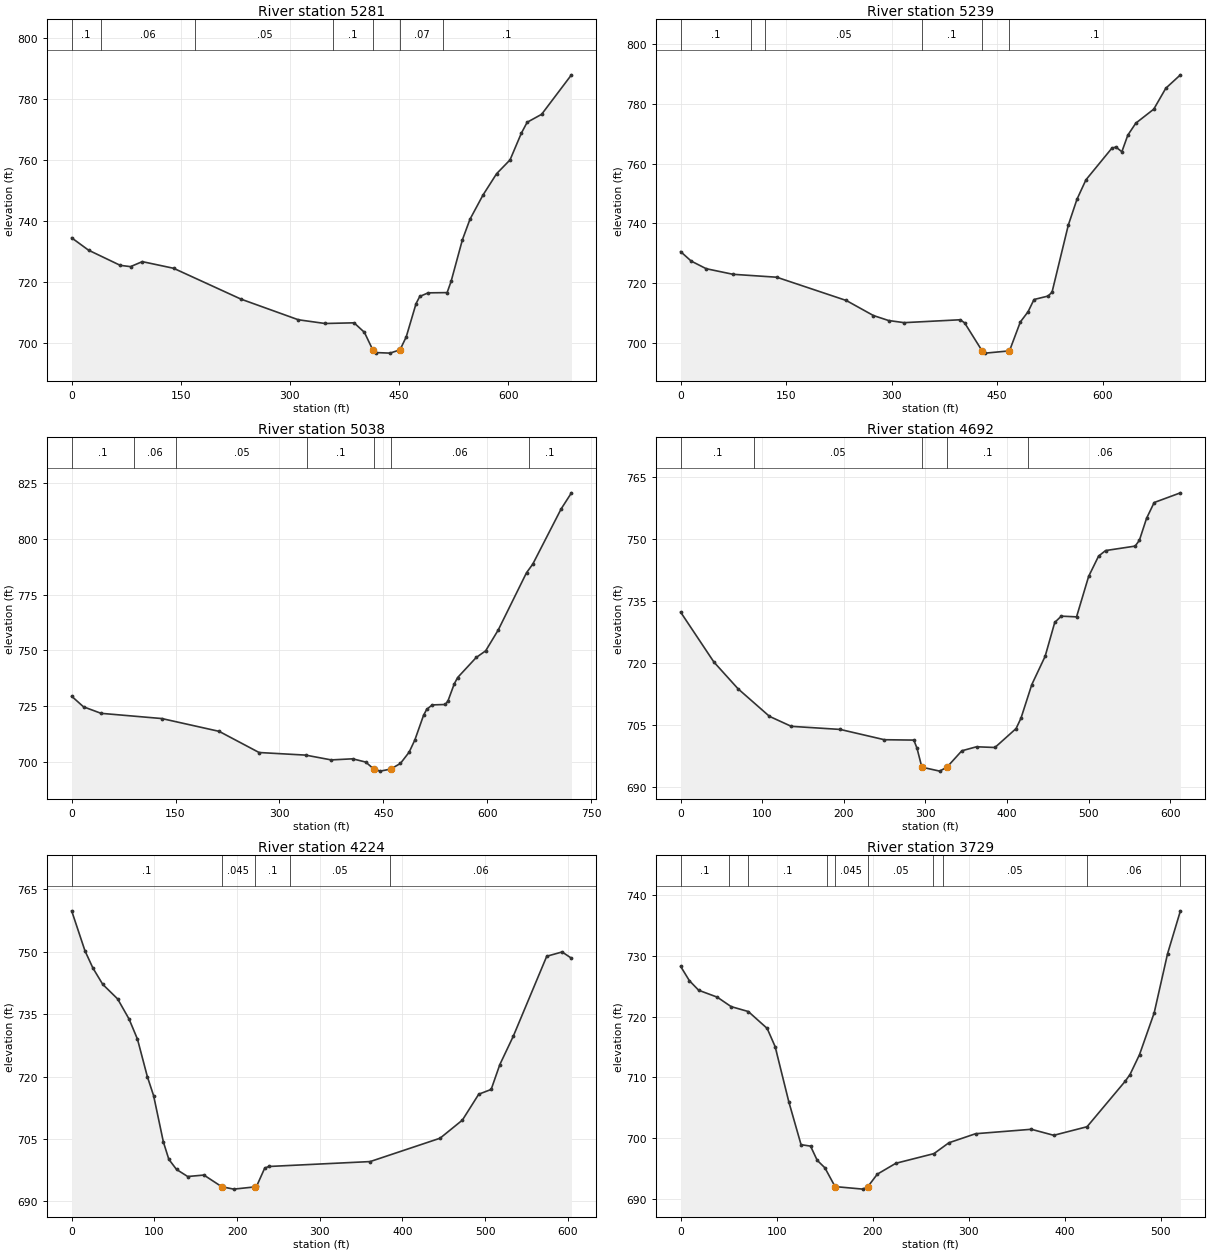
Type RM Length L Ch R = 1 ,5281    ,41.5,42.2,41.7
XS GIS Cut Line= 5
1631995.44984237386112.3745963961632128.67251328386260.440200753
1632195.63037542386287.2648736151632230.50645402386303.785121375
1632518.69299829386546.999880072
#Sta/Elev= 30
       0  734.36    23.2  730.31    66.8  725.33    80.9  724.91    97.1  726.55
   140.1  724.37     233  714.23   311.6  707.48   348.3  706.26   388.2  706.48
   402.4  703.36   413.8  697.66   417.7  696.73   437.6  696.54   451.4697.6391
   459.9  701.88   473.4  712.79   478.5  715.13     490  716.31   516.1  716.39
   521.6  720.11   537.1  733.72   547.5  740.45   565.3  748.35   584.1  755.39
   602.6  759.93   618.1  768.67   626.1  772.26     646  774.87     687  787.82
#Mann= 7 ,-1,0
       0      .1       0      40     .06       0     170     .05       0
   359.9      .1       0   413.8    .045       0   451.4     .07       0
   509.9      .1       0
Bank Sta=413.8,451.4
XS Rating Curve= 0 ,0
Exp/Cntr(USF)=0,0
Exp/Cntr=0.3,0.1

Type RM Length L Ch R = 1 ,5239    ,191.8,201.2,208.9
XS GIS Cut Line= 5
1631947.77567059386151.7376558751632106.23760892386299.191399204
1632179.56902343386327.6477014741632214.44510203386344.167949234
 1632502.6316463386587.382707932
#Sta/Elev= 30
       0  730.51      15  727.35    36.4  724.79    74.4  722.92   136.7  721.94
   235.6  714.15   274.2  709.11   295.7  707.45   317.8  706.73   397.6   707.7
   403.9  706.66   428.8  697.28   433.5  696.53   467.7697.2889   483.1  706.95
   494.1  710.38   502.6  714.48   522.5  715.63   528.2  716.92   551.3  739.35
   563.7  748.05   576.4  754.53   613.3  765.13     619  765.53   627.5  763.94
     636  769.51   647.4  773.52   672.9   778.2     690   785.2   710.8  789.69
#Mann= 6 ,-1,0
       0      .1       0     100     .06       0     120     .05       0
  343.71      .1       0   428.8    .045       0   467.7      .1       0
Bank Sta=428.8,467.7
XS Rating Curve= 0 ,0
Exp/Cntr(USF)=0,0
Exp/Cntr=0.3,0.1

Type RM Length L Ch R = 1 ,5038    ,348.2,345.6,341.8
XS GIS Cut Line= 4
1631916.81263636386171.6953031371632097.82854517386358.282411963
1632170.10806029386607.8203703451632265.49268434386785.659791845
#Sta/Elev= 30
       0  729.48    17.1  724.73    42.5  721.81   130.2  719.47   212.9  713.73
   270.6  704.24   337.9  703.07   374.8  700.92   405.7  701.41   424.7  699.94
   436.3696.7768   445.5  695.89   460.6  696.81   474.7  699.35   487.2  704.37
   495.5  709.87     508  720.87   512.6   723.6   520.6  725.59   539.5  725.78
   543.3  727.37   552.3  734.95   557.2  737.84   584.1  746.86   597.7  749.83
   615.9   759.2   656.7  784.86   665.8  788.76   706.7  813.49   721.6   820.7
#Mann= 7 ,-1,0
       0      .1       0      90     .06       0     150     .05       0
  339.96      .1       0   436.3    .045       0   460.6     .06       0
  659.76      .1       0
Bank Sta=436.3,460.6
XS Rating Curve= 0 ,0
Exp/Cntr(USF)=0,0
Exp/Cntr=0.3,0.1

Type RM Length L Ch R = 1 ,4692    ,470.3,468.5,462.5
XS GIS Cut Line= 6
 1631674.1685115386355.4060476371631793.20895583386582.327837894
1631839.66391541386670.8827788931631874.50538116386737.298656548
1631915.15293765386814.784065882  1631959.236839386897.525042141
#Sta/Elev= 30
       0  732.27    40.8  720.18    70.4  713.71   108.9  707.04   135.6  704.63
   195.5  703.88   249.7  701.39   285.8   701.3   289.7  699.32   295.6  694.75
   317.5  693.79   326.6694.7916   344.6  698.71   362.6  699.68   385.2  699.51
   411.1  704.09   417.1   706.6   430.4  714.75   446.7  721.57   458.5  729.78
   466.5  731.29   485.2  731.12     500   740.9   512.2  745.82   520.8  747.16
     557  748.24   562.2  749.64     571  754.96   580.3  758.78   612.5  761.13
#Mann= 5 ,-1,0
       0      .1       0      90     .05       0   295.6    .045       0
   326.6      .1       0  426.25     .06       0
Bank Sta=295.6,326.6
XS Rating Curve= 0 ,0
Exp/Cntr(USF)=0,0
Exp/Cntr=0.3,0.1

Type RM Length L Ch R = 1 ,4224    ,493.4,494.6,495.8
XS GIS Cut Line= 4
1631280.34287308386606.0714663261631321.37730023386691.088425747
1631499.51620686386942.4967499391631633.93491009387092.959120936
#Sta/Elev= 30
       0  759.81    16.1   750.2    25.6   746.1    37.6  742.14    55.6  738.64
    69.4  733.81    79.6  728.96    91.5  719.98    99.1  715.39   110.9  704.27
   117.5   700.1   126.8  697.67   140.3  695.97   159.9  696.32   181.6693.5027
     196  692.94   221.4693.4728   223.6  693.63   233.4  697.98   238.3  698.38
   360.9  699.56   445.4  705.17   472.4  709.52   492.2  715.75   507.2  716.89
   517.7  722.87     534   729.7   574.4  748.89     593  749.93   604.3  748.42
#Mann= 5 ,-1,0
       0      .1       0   181.6    .045       0   221.4      .1       0
   264.4     .05       0   384.4     .06       0
Bank Sta=181.6,221.4
XS Rating Curve= 0 ,0
Exp/Cntr(USF)=0,0
Exp/Cntr=0.3,0.1

Type RM Length L Ch R = 1 ,3729    ,133.2,136,139.8
XS GIS Cut Line= 3
1630919.44123591386881.9937929951630950.64614835386990.293194981
1631192.02532396387318.862567108
#Sta/Elev= 30
       0  728.26     9.1  725.91    18.8  724.33    38.1   723.2    52.6  721.64
    70.5  720.83    90.1  718.06    98.4  715.07   112.7  705.96   125.4  698.94
   135.3   698.7   142.2  696.37   150.2  695.14   160.8692.0467   189.8  691.63
   194.9  692.03   204.8  694.09   224.1  695.88   263.8  697.47   279.3  699.25
   307.1  700.74   365.2  701.47   388.5  700.48   423.2  701.89   462.9  709.37
   467.9  710.47   477.8  713.74   493.1  720.62     507  730.33   520.4  737.39
#Mann= 10 ,-1,0
       0      .1       0      50     .05       0      70      .1       0
  152.71     .05       0   160.8    .045       0   194.9     .05       0
  262.71      .1       0  272.71     .05       0  422.71     .06       0
  520.41      .1       0
Bank Sta=160.8,194.9
XS Rating Curve= 0 ,0
Exp/Cntr(USF)=0,0
Exp/Cntr=0.3,0.1

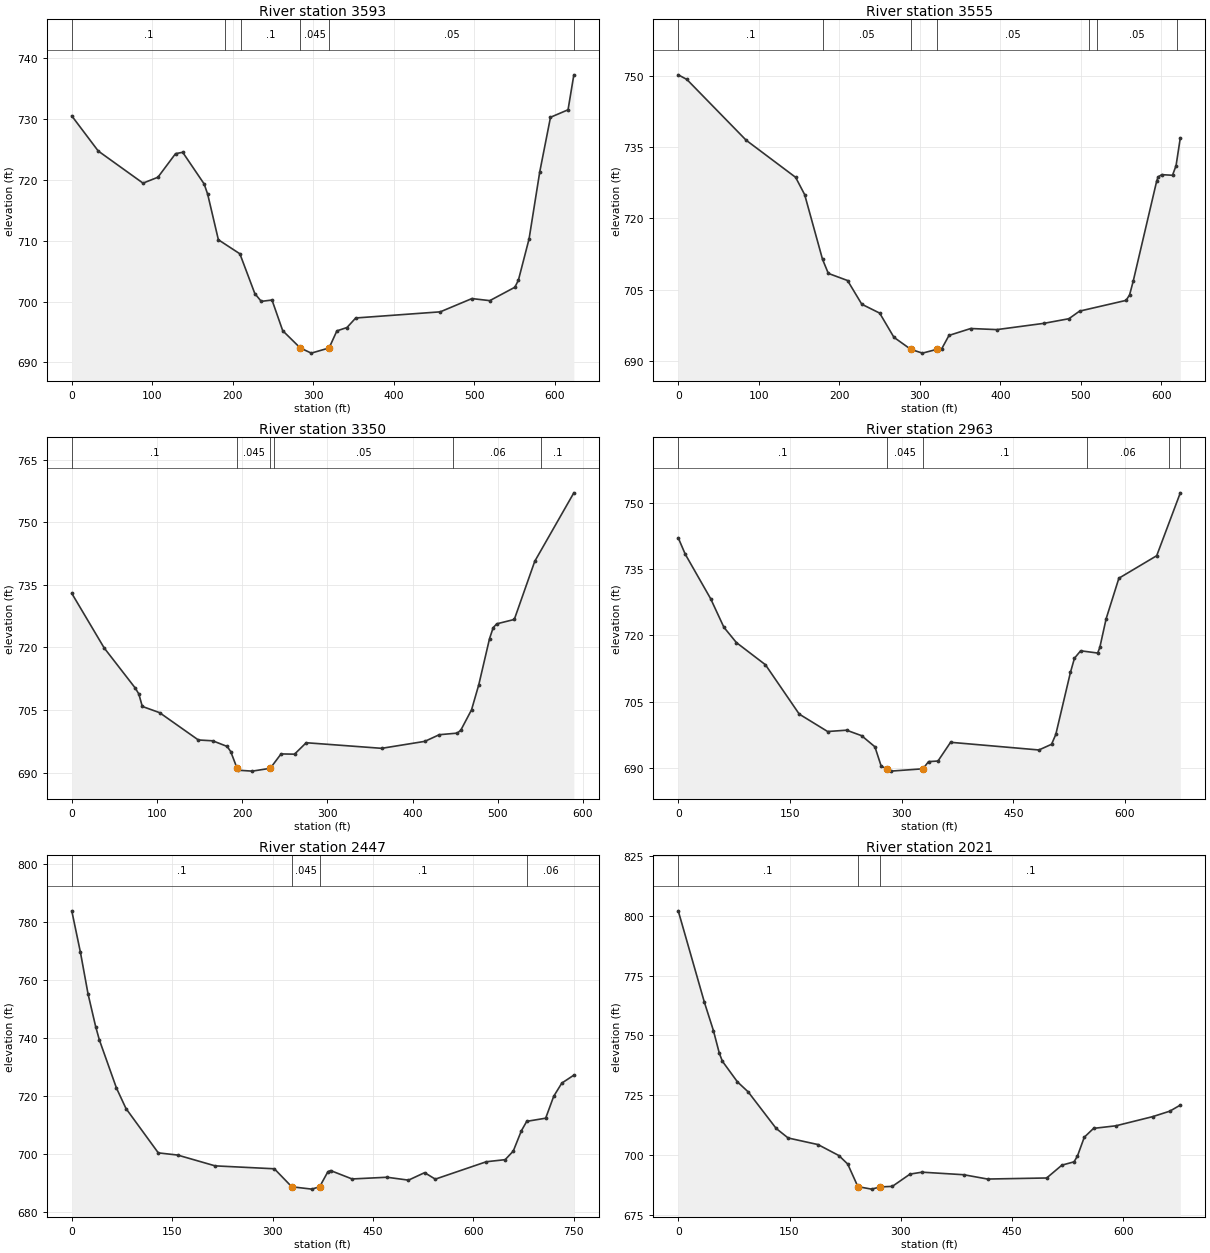
Type RM Length L Ch R = 1 ,3593    ,37.8,37.8,38.1
XS GIS Cut Line= 2
1630749.89113421 386852.260229051631019.23918041387414.677122095
#Sta/Elev= 30
       0  730.55    32.9  724.77    88.5  719.49     107  720.46   128.9  724.34
   137.8  724.56   164.4  719.36   168.8  717.67   182.1  710.18   208.8  707.87
   227.4  701.32   235.4  700.05   248.7  700.27     262  695.23   283.8  692.39
   297.5  691.54   319.6  692.39   329.3   695.2   341.8  695.75   352.7  697.32
   457.7  698.33     497  700.51   519.2  700.17   550.3  702.37   554.7  703.52
     568  710.33   581.3  721.38   594.6  730.32   616.4  731.55   623.6   737.3
#Mann= 6 ,-1,0
       0      .1       0     190     .05       0     210      .1       0
   283.8    .045       0   319.6     .05       0  623.59     .06       0
Bank Sta=283.8,319.6
XS Rating Curve= 0 ,0
Exp/Cntr(USF)=0,0
Exp/Cntr=0.3,0.1

Type RM Length L Ch R = 1 ,3555    ,203.1,205.4,206.8
XS GIS Cut Line= 2
1630713.14493775386862.8971760121630982.49298396387425.314069056
#Sta/Elev= 30
       0  750.19    10.7  749.22    84.4  736.42   145.8  728.62     157  724.99
   179.2  711.37   186.4   708.4   210.3   706.9     228  701.91   250.2  700.04
   267.9  694.95   288.8692.4225   303.3  691.62   321.1  692.41   327.3  692.55
   336.3  695.35   363.3   696.8   395.8  696.57   454.2  697.89   485.2  698.86
   498.5  700.46   556.2  702.72   560.6  703.88   565.1  706.77   594.2  727.79
   596.1  728.71   600.6  729.18   613.9  729.05   618.3  731.06   623.6  736.93
#Mann= 7 ,-1,0
       0      .1       0     180     .05       0   288.8    .045       0
   321.1     .05       0     510     .06       0     520     .05       0
     620     .06       0
Bank Sta=288.8,321.1
XS Rating Curve= 0 ,0
Exp/Cntr(USF)=0,0
Exp/Cntr=0.3,0.1

Type RM Length L Ch R = 1 ,3350    ,373.7,387.3,370.9
XS GIS Cut Line= 4
1630602.80315384386991.2109865231630626.66573394387116.948427812
1630748.73200906387480.393878544 1630749.6498006387558.406159636
#Sta/Elev= 30
       0  732.95      38  719.89    74.6  710.25    78.7  708.86    82.8  705.87
   103.1  704.38   148.6  697.84   165.5  697.64   182.4  696.29   186.6  695.06
   193.9691.1442   195.1   690.6   211.9  690.38     233  691.06   245.7   694.5
   261.5  694.44   275.2  697.18   363.8  695.84   414.5  697.51   431.4   699.1
   452.5  699.48   456.7  700.19   469.3  705.06   477.8  711.07   490.4  722.08
   494.7  724.73   498.9  725.65   519.5   726.7   543.5  740.62   589.4  757.02
#Mann= 6 ,-1,0
       0      .1       0   193.9    .045       0     233      .1       0
  237.98     .05       0  447.98     .06       0  551.38      .1       0
Bank Sta=193.9,233
XS Rating Curve= 0 ,0
Exp/Cntr(USF)=0,0
Exp/Cntr=0.3,0.1

Type RM Length L Ch R = 1 ,2963    ,536.5,515.3,485.1
XS GIS Cut Line= 4
1630258.56041106387034.2836097811630303.56326952387171.461476469
 1630429.8499612387534.5530842151630545.29677515387622.915798578
#Sta/Elev= 30
       0  742.08     9.4  738.38    43.5   728.3    61.3  721.83    78.1  718.36
   117.1  713.34   162.5  702.16   200.6  698.22     226  698.52   246.2  697.28
   264.1  694.76   272.6  690.34     280  689.83   285.3  689.25   328.6689.7768
   336.1   691.4   348.8  691.54   365.7  695.78   484.3  694.04   501.3  695.33
     507  697.56   526.7  711.64   532.1  714.83   540.4   716.5   563.2  715.99
   566.1  717.25   574.6  723.76   591.7  732.93   642.5  738.03   674.2  752.27
#Mann= 6 ,-1,0
       0      .1       0     280    .045       0   328.6      .1       0
   548.8     .06       0   658.8     .07       0  674.18      .1       0
Bank Sta=280,328.6
XS Rating Curve= 0 ,0
Exp/Cntr(USF)=0,0
Exp/Cntr=0.3,0.1

Type RM Length L Ch R = 1 ,2447    ,412.2,426.3,422
XS GIS Cut Line= 4
1629725.01896125387521.233785838 1629831.2184916387637.083960928
1630302.51506946387673.7059564551630421.97271498387688.362172766
#Sta/Elev= 30
       0  783.89      13  769.51    24.3  755.23    35.7  743.94    41.3   739.3
    66.8  722.72      81  715.67   129.3  700.36   158.1  699.61   214.2  695.88
   302.7  694.87   328.7  688.66   358.7  687.85   370.4688.6853   382.7  693.85
   386.7  694.26   418.8  691.36     471  691.95   503.1  690.95   527.2  693.53
   543.2   691.3   619.4   697.3   647.6  698.02   659.7  700.99   671.8  707.98
   679.8  711.24   708.1  712.33   720.1  719.88   732.2  724.44   750.2  727.18
#Mann= 4 ,-1,0
       0      .1       0   328.7    .045       0   370.4      .1       0
  679.88     .06       0
Bank Sta=328.7,370.4
XS Rating Curve= 0 ,0
Exp/Cntr(USF)=0,0
Exp/Cntr=0.3,0.1

Type RM Length L Ch R = 1 ,2021    ,510.6,517.6,522.8
XS GIS Cut Line= 4
1629517.07304487387934.7770644691629688.84971659 387955.40972455
1630045.74238835387979.3540102411630172.53927099388051.595301084
#Sta/Elev= 30
       0  802.13    35.3  763.83    47.4  752.07    55.4  742.54    59.5  739.23
    79.8  730.59    94.2  726.43     132  711.11   148.1  707.13   188.3  704.38
   216.4   699.8   228.4  696.23   242.1686.7791   260.5  685.74   272.5  686.67
   288.5  686.89   312.4  692.03   328.6  692.83   384.8  691.76   416.8  689.96
   496.5   690.4     517  695.76   533.4  697.16     538  699.59   547.2  707.45
   559.7  711.15   589.7  712.22   639.3  716.05   662.4  718.34   676.6  720.88
#Mann= 3 ,-1,0
       0      .1       0   242.1    .045       0   272.5      .1       0
Bank Sta=242.1,272.5
XS Rating Curve= 0 ,0
Exp/Cntr(USF)=0,0
Exp/Cntr=0.3,0.1