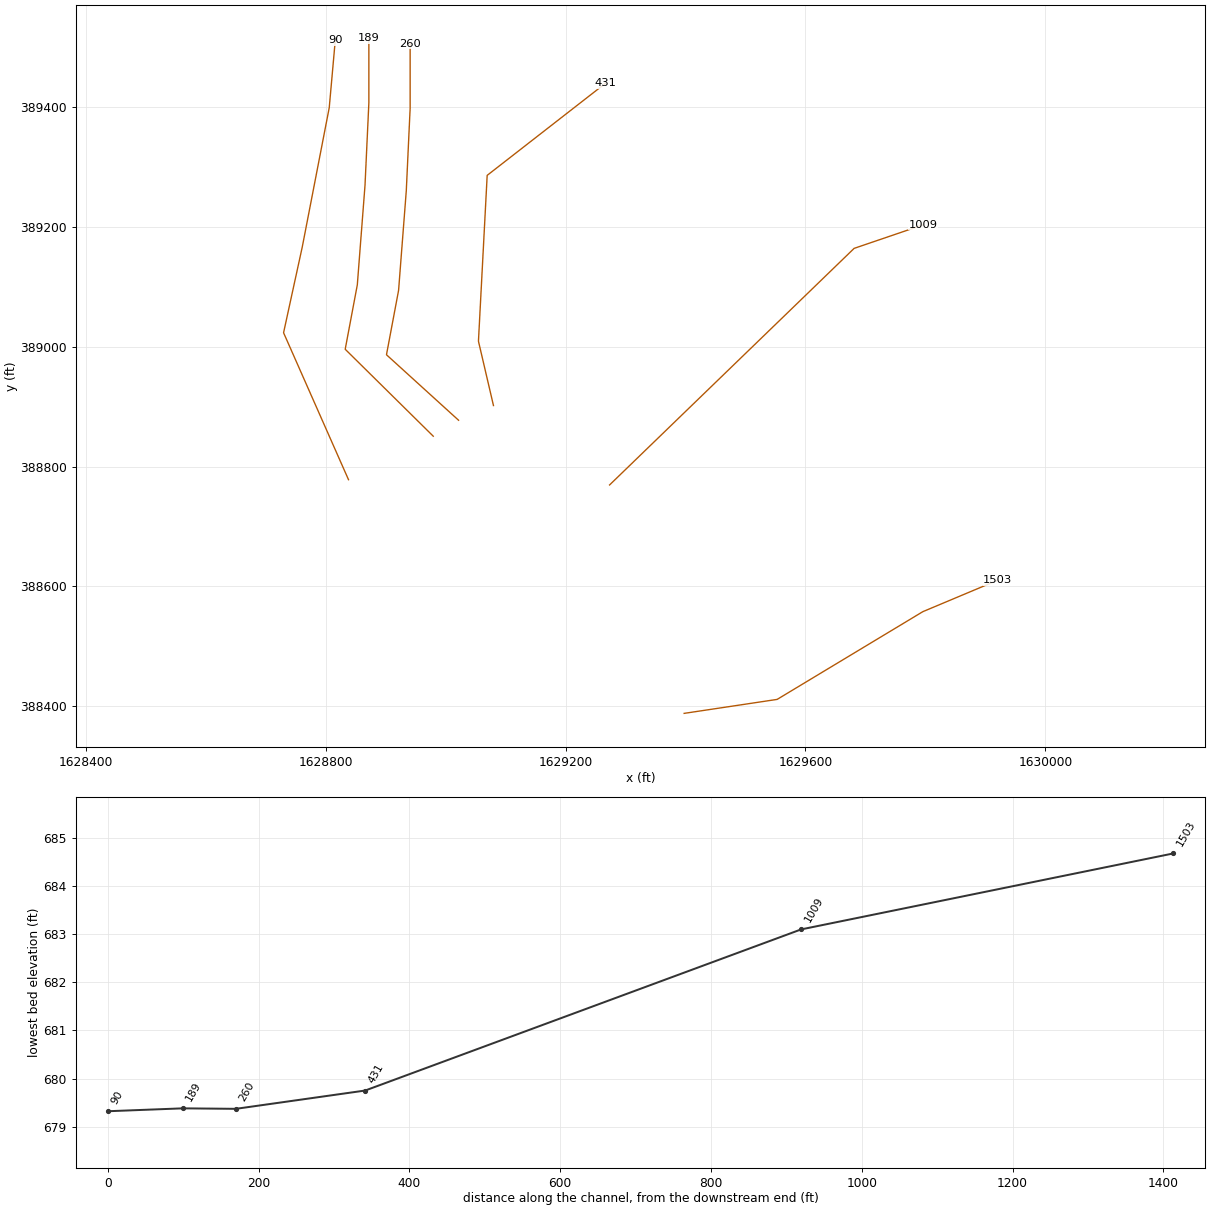
HEC-RAS study PINEYFK.prj: PINEYFK

--- PINEYFK.g01 (geometry) --- (continued)

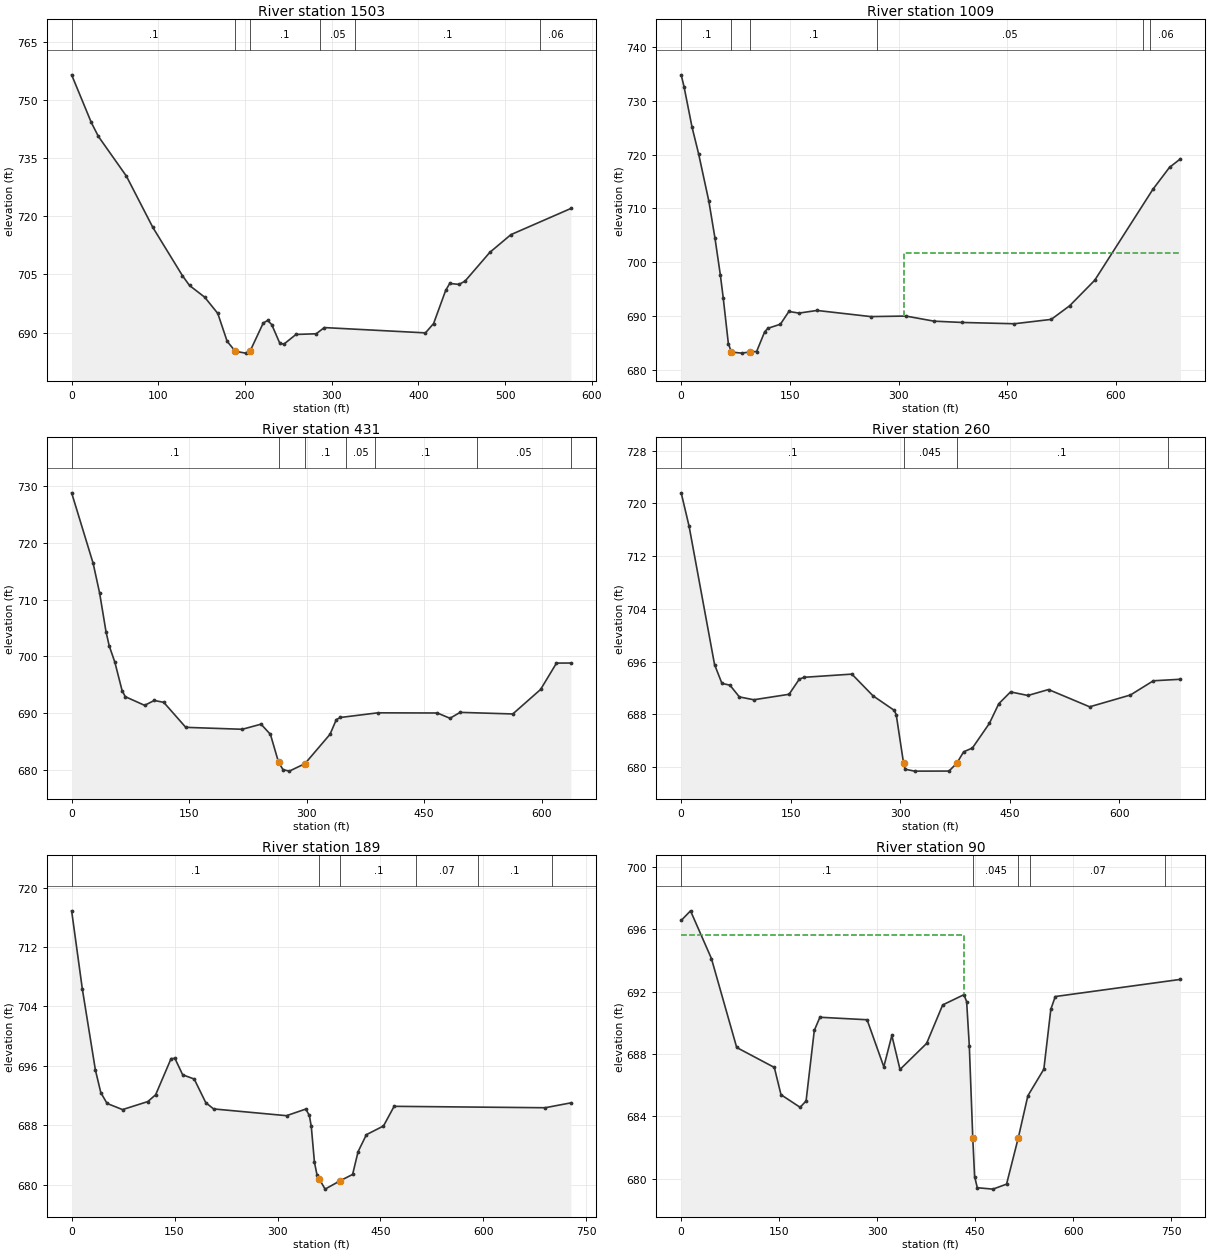
Type RM Length L Ch R = 1 ,1503    ,488.3,493.9,494.2
XS GIS Cut Line= 4
1629397.65990216388388.3933051231629552.77299259388411.699710476
1629795.74287966388558.0113261771629920.71886961388610.505216382
#Sta/Elev= 30
       0  756.55    22.7  744.24    30.8  740.67    63.2  730.39    93.7  717.14
   127.9  704.66     136  702.15   153.5  699.13   168.6  694.94   179.4  687.74
   188.8  685.16   200.7  684.68     206  685.26   221.1  692.47   226.1  693.11
   230.8  692.07   240.1  687.27   244.8  686.98   258.8   689.5   282.2  689.68
   291.5  691.28   408.2  689.91   417.6  692.33   431.6  700.92   436.2  702.67
     447  702.43   453.9  703.29   482.4  710.69   506.8  715.28     576  722.04
#Mann= 6 ,-1,0
       0      .1       0   188.8    .045       0     206      .1       0
  286.85     .05       0  326.85      .1       0  540.48     .06       0
Bank Sta=188.8,206
XS Rating Curve= 0 ,0
Exp/Cntr(USF)=0,0
Exp/Cntr=0.3,0.1

Type RM Length L Ch R = 1 ,1009    ,564.5,578.4,591.2
XS GIS Cut Line= 3
1629273.33078495388769.3573561461629681.17064139 389163.92684179
 1629796.0643882389203.088603355
#Sta/Elev= 30
       0  734.82     3.9  732.65      15  725.09      24  720.18    38.2  711.32
    46.6  704.51      54  697.68      58   693.4    65.1  684.88    69.3   683.3
    83.4   683.1    94.7  683.32   104.1   683.4   115.2  687.06   119.6  687.71
   136.9  688.47   148.6  690.84   162.6  690.54   187.5  691.03   261.6  689.89
     310  689.99   348.9  689.04   387.9   688.8   459.7  688.56   510.6  689.37
     536   691.9   570.6  696.64   650.9  713.55   673.8  717.62   688.9  719.21
#Mann= 6 ,-1,0
       0      .1       0    69.3    .045       0    94.7      .1       0
     270     .05       0  637.47      .1       0  647.47     .06       0
#XS Ineff= 2 , 0
                          307.38          701.65
Permanent Ineff=
       F       F
Bank Sta=69.3,94.7
XS Rating Curve= 0 ,0
Exp/Cntr(USF)=0,0
Exp/Cntr=0.3,0.1

Type RM Length L Ch R = 1 ,431     ,168.6,171.4,149.4
XS GIS Cut Line= 4
 1629079.6576935388901.7889014051629054.61879207389009.078911659
1629069.17348673389285.6898421581629266.66405395 389439.37314946
#Sta/Elev= 30
       0  728.82    27.5  716.37    35.7  711.17    43.9  704.33      48  701.83
    55.2  698.95    64.4  693.96    68.5  692.88    93.2  691.35   105.5  692.21
   117.6  691.88   145.7  687.47   217.9  687.13   241.8  688.03   253.8  686.23
   264.2681.2975   269.9  680.01   277.9  679.75   297.9  681.07   329.9  686.25
   337.9  688.83   343.2  689.21   390.9  690.03   466.9     690     483  689.07
     496  690.11   563.2  689.83   598.7  694.15     619   698.8   637.4  698.81
#Mann= 7 ,-1,0
       0      .1       0   264.2    .045       0   297.9      .1       0
  350.17     .05       0  387.17      .1       0  517.17     .05       0
  637.17      .1       0
Bank Sta=264.2,297.9
XS Rating Curve= 0 ,0
Exp/Cntr(USF)=0,0
Exp/Cntr=0.3,0.1

Type RM Length L Ch R = 1 ,260     ,72.1,70.6,74.3
XS GIS Cut Line= 6
1629021.44832653388877.272605855 1628901.2176345388986.489799383
1628921.40904843389093.8714098271628934.25813002389259.991678974
1628940.68267082389397.6604103121628940.68267082389505.042020756
#Sta/Elev= 30
       0   721.6    10.8  716.55    45.7  695.54    55.8  692.68    66.7  692.42
    79.7  690.63    99.5   690.2   147.7  691.03   161.8  693.34   168.6  693.61
   233.7  694.09   262.6   690.8   291.6   688.6   294.4  687.94   304.5680.5302
   306.5  679.66   319.5  679.37   366.6  679.38   377.2  680.55   386.7   682.3
   398.7  682.88   421.9  686.61   434.8   689.6   450.9  691.39   474.7  690.85
   502.9  691.75   559.2  689.13     615  690.92   646.4  693.08   683.5  693.31
#Mann= 4 ,-1,0
       0      .1       0   304.5    .045       0   377.2      .1       0
  666.13     .05       0
Bank Sta=304.5,377.2
XS Rating Curve= 0 ,0
Exp/Cntr(USF)=0,0
Exp/Cntr=0.3,0.1

Type RM Length L Ch R = 1 ,189     ,102.1,99.2,117.9
XS GIS Cut Line= 6
1628979.22991559388850.6566511291628832.38326883388995.667714805
1628852.57468276389103.0493252491628865.42376435389269.169594397
1628871.84830515389406.8383257351628871.84830515389514.219936179
#Sta/Elev= 30
       0  716.89    15.6  706.36    34.6  695.45    42.5  692.39    51.6  690.93
    74.2   690.1     111  691.18   122.4   692.1   144.9  696.97   150.5     697
   161.8  694.79   178.6  694.22   195.5  691.03   206.9  690.19   313.1  689.28
   341.2  690.17   346.4  689.31   349.2  687.83   353.8  683.01   357.6  681.27
     361680.7317   369.3  679.38   391.7  680.53   409.4  681.36   417.4  684.43
   429.5  686.72   454.4  687.89   469.9  690.54     690  690.35   727.5  691.01
#Mann= 6 ,-1,0
       0      .1       0     361    .045       0   391.7      .1       0
  502.26     .07       0  592.26      .1       0  700.08     .05       0
Bank Sta=361,391.7
XS Rating Curve= 0 ,0
Exp/Cntr(USF)=0,0
Exp/Cntr=0.3,0.1

Type RM Length L Ch R = 1 ,90      ,,,
XS GIS Cut Line= 5
1628837.89001808388778.151119291 1628729.5906161389023.201461073
1628760.79552853389166.376941665 1628805.7673141389398.578201855
1628815.86302107389511.466561552
#Sta/Elev= 30
       0  696.56    14.3  697.18    46.3  694.12      85  688.41   142.6  687.13
   152.8  685.38   182.1  684.57   191.2  684.98   203.8  689.51   212.4  690.35
   284.6  690.19   310.2  687.17   322.5  689.18     335     687   375.7  688.67
   400.3  691.14   432.9   691.8     437  691.35   441.1   688.5   446.4  682.59
   449.2  680.13   453.3  679.41   477.2  679.32   498.1  679.64   516.1  682.62
   530.7  685.31   555.2  687.02   565.9  690.87   572.7  691.68   764.3  692.78
#Mann= 5 ,-1,0
       0      .1       0   446.4    .045       0   516.1      .1       0
  534.45     .07       0  740.97      .1       0
#XS Ineff= 2 , 0
          432.96  695.65
Permanent Ineff=
       F       F
Bank Sta=446.4,516.1
XS Rating Curve= 0 ,0
Exp/Cntr(USF)=0,0
Exp/Cntr=0.3,0.1
LCMann Table=0

Chan Stop Cuts=-1
Use User Specified Reach Order=0
Composite Channel Slope=5